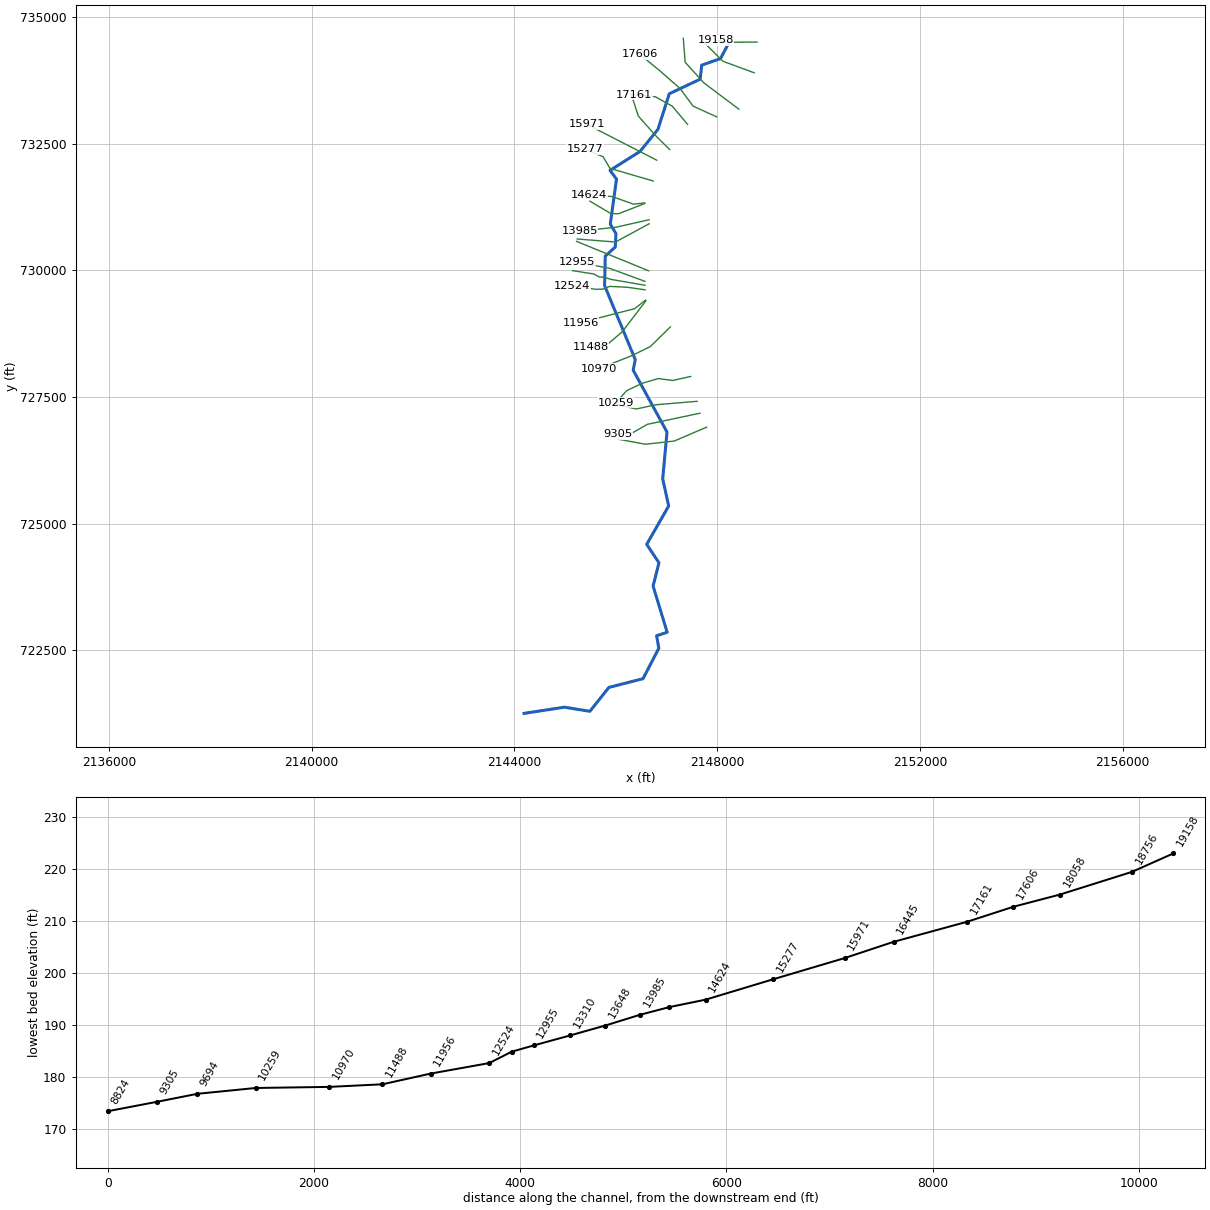
--- R-2829B_Basin15_Strm7_NC540.prj (project) ---

Proj Title=R-2829B_Basin15_Strm7_I540
Current Plan=p04
Default Exp/Contr=0.3,0.1
English Units
Geom File=g01
Geom File=g03
Geom File=g04
Flow File=f01
Plan File=p01
Plan File=p03
Plan File=p04
Y Axis Title=Elevation
X Axis Title(PF)=Main Channel Distance
X Axis Title(XS)=Station
BEGIN DESCRIPTION:
END DESCRIPTION:
DSS File=dss
DSS Export Rating Curves= 0
DSS Export Rating Curve Sorted= 0
DSS Export Volume Flow Curves= 0
DXF OffsetX= 0
DXF OffsetY= 0
DXF ScaleX= 1
DXF ScaleY= 10

--- R-2829B_Basin15_Strm7_NC540.p04 (plan) ---

Plan Title=Revised
Program Version=6.20
Short Identifier=REV
Geom File=g04
Flow File=f01
Subcritical Flow
K Sum by GR= 0
Std Step Tol= 0.0001
Critical Tol= 0.0001
Num of Std Step Trials= 40
Max Error Tol= 0.1
Flow Tol Ratio= 0.0001
Split Flow NTrial= 100
Split Flow Tol= 0.001
Split Flow Ratio= 0.0001
Log Output Level= 0
Friction Slope Method= 1
Unsteady Friction Slope Method= 2
Unsteady Bridges Friction Slope Method= 1
Parabolic Critical Depth
Global Vel Dist= 0 , 0 , 0
Global Log Level= 0
CheckData=True
Encroach Param= 0 ,10,10, 2
Encroach River=Basin15 Stream7
Encroach Reach=Main
Encroach Node=19158
       1     505     595
Encroach Node=18756
       1     710     820
Encroach Node=18058
       1     930    1170
Encroach Node=17606
       1     875    1115
Encroach Node=17161
       1     530     700
Encroach Node=16445
       1     420     600
Encroach Node=15971
       1     345     570
Encroach Node=15277
       1     710     895
Encroach Node=14624
       1     485     640
Encroach Node=14272
       1     610     765
Encroach Node=13985
       1     680     850
Encroach Node=13648
       1     740     930
Encroach Node=13310
       1     690     920
Encroach Node=12955
       1     680     870
Encroach Node=12741
       1  724.75  894.75
Encroach Node=12524
       1  720.75  860.75
Encroach Node=11956
       1     627     762
Encroach Node=11488
       1   768.9     898
Encroach Node=10970
       1     900    1050
Encroach Node=10259
       1     880    1050
Encroach Node=9694
       1     780     950
Encroach Node=9305
       1     700     890
Encroach Node=8824
       1     800    1000
Encroach Node=8350
       1     800    1110
Encroach Node=7623
       1    1185    1455
Encroach Node=7129
       1     755    1005
Encroach Node=6485
       1     760    1050
Encroach Node=5978
       1     700     990
Encroach Node=5455
       1     855    1020
Encroach Node=4965
       1     710     932
Encroach Node=4454
       1     545     695
Encroach Node=3782
       1     790     970
Encroach Node=3406
       1     950    1170
Encroach Node=3226
       1    4899    5173
Encroach Node=3119
       1    4850    5100
Encroach Node=2900
       1    4910    5171
Encroach Node=2852
       1    4892    5136
Encroach Node=2777
       1    4955    5193
Encroach Node=2745
       1    4871    5155
Encroach Node=2456
       1    4930    5075
Encroach Node=2398
       1    4956    5111
Encroach Node=2367
       1    4950    5116
Encroach Node=2320
       1    4948    5095
Encroach Node=2160
       1    4908    5056
Encroach Node=2044
       1    4863    5035
Encroach Node=1855
       1     520     720
Encroach Node=1457
       1     350     630
Encroach Node=1081
       1     550     710
Encroach Node=782
       1   571.3   677.7
Encroach Node=469
       1     598     750
Encroach Node=92
       1   824.2   901.9
Computation Interval=1HOUR
Output Interval=1HOUR
Instantaneous Interval=1HOUR
Mapping Interval=1HOUR
Computation Time Step Use Courant=        0
Computation Time Step Use Time Series=    0
Computation Time Step Count To Double=0
Computation Time Step Max Doubling=0
Computation Time Step Max Halving=0
Computation Time Step Residence Courant=0
Run HTab= 0
Run UNet= 0
Run Sediment= 0
Run PostProcess= 0
Run WQNet= 0
Run RASMapper= 0
UNET Theta= 1
UNET Theta Warmup= 1
UNET ZTol= 0.02
UNET ZSATol= 0.05
UNET MxIter= 20
UNET Max Iter WO Improvement= 0
UNET MaxInSteps= 0
UNET DtIC= 0
UNET DtMin= 0
UNET MaxCRTS= 20
UNET WFStab= 2
UNET SFStab= 1
UNET WFX= 1
UNET SFX= 1
UNET Gravity=32.174
UNET 1D Methodology=Finite Difference
UNET DSS MLevel= 4
UNET Pardiso=0
UNET DZMax Abort= 100
UNET Use Existing IB Tables=-1
UNET Froude Reduction=False
UNET Froude Limit= 1
UNET Froude Power= 10
UNET D1 Cores= 0
UNET WindReference=Eulerian
UNET WindDragFormulation=Hsu (1988)
UNET D2 Coriolis=0
UNET D2 Cores= 0
UNET D2 Theta= 1
UNET D2 Theta Warmup= 1
UNET D2 Z Tol= 0.01
UNET D2 Volume Tol= 0.01
UNET D2 Max Iterations= 20
UNET D2 Equation= 0
UNET D2 RampUpFraction=0.1
UNET D2 TimeSlices= 1
UNET D2 Turbulence Formulation=Non-Conservative (original)
UNET D2 Eddy Viscosity=0.3
UNET D2 Transverse Eddy Viscosity=0.1
UNET D2 Smagorinsky Mixing=0
UNET D2 BCVolumeCheck=0
UNET D2 Cores=0
UNET D2 SolverType=PARDISO (Direct)
UNET D2 Minimum Iterations= 2147483647
UNET D2 Maximum Iterations= 2147483647
UNET D2 Restart Number= 10
UNET D2 Relaxation Coeff=1.3
UNET D2 SOR Precondition Iterations= 10
UNET D2 ILUT Maximum Fill= 8
UNET D2 ILUT Tolerance=1E-08
UNET D1D2 MaxIter= 0
UNET D1D2 ZTol=0.01
UNET D1D2 QTol=0.1
UNET D1D2 MinQTol=1
DSS File=dss
Write IC File= 0
Write IC File at Fixed DateTime=0
Write IC File at Sim End=0
Echo Input=False
Echo Parameters=False
Echo Output=False
Write Detailed= 0
HDF Write Warmup=0
HDF Write Time Slices=0
HDF Flush=0
HDF Compression= 1
HDF Chunk Size= 1
HDF Spatial Parts= 1
HDF Use Max Rows=0
HDF Fixed Rows= 1
Calibration Method= 0
Calibration Iterations= 20
Calibration Max Change=0.05
Calibration Tolerance=0.2
Calibration Maximum=1.5
Calibration Minimum=0.5
Calibration Optimization Method= 1
WQ AD Non Conservative
WQ ULTIMATE=-1
WQ Max Comp Step=1HOUR
WQ Output Interval=15MIN
WQ Output Selected Increments= 0
WQ Output face flow=0
WQ Output face velocity=0
WQ Output face area=0
WQ Output face dispersion=0
WQ Output cell volume=0
WQ Output cell surface area=0
WQ Output cell continuity=0
WQ Output cumulative cell continuity=0
WQ Output face conc=0
WQ Output face dconc_dx=0
WQ Output face courant=0
WQ Output face peclet=0
WQ Output face adv mass=0
WQ Output face disp mass=0
WQ Output cell mass=0
WQ Output cell source sink temp=0
WQ Output nsm pathways=0
WQ Output nsm derived pathways=0
WQ Create Restart=0
WQ Fixed Restart=0
WQ System Summary=0
WQ Write To DSS=0
Sorting and Armoring Iterations= 10
XS Update Threshold= 0.02
Bed Roughness Predictor= 0
Hydraulics Update Threshold= 0.02
Energy Slope Method= 1
Volume Change Method= 0
Sediment Retention Method= 0
Sediment TS Multiplier= 1
Warm Up Method= 0
XS Weighting Method= 0
Number of US Weighted Cross Sections= 1
Number of DS Weighted Cross Sections= 1
Upstream XS Weight=0.25
Main XS Weight=0.5
Downstream XS Weight=0.25
Number of DS XS's Weighted with US Boundary= 1
Upstream Boundary Weight= 1
Weight of XSs Associated with US Boundary= 0
Number of US XS's Weighted with DS Boundary= 1
Downstream Boundary Weight= 0.5
Weight of XSs Associated with DS Boundary= 0.5
Percentile Method= 0
Sediment Output Level= 4
Mass or Volume Output= 0
Output Increment Type= 1
Profile and TS Output Increment= 10
Transport Output Increment 1
XS Output Flag= 0
XS Output Increment= 10
Read HDF5 Sediment Hotstart= 0
Sediment Hotstart Type= 0
Write Gradation File= 0
Read Gradation Hotstart= 0
Write HDF5 File= 1
Write Binary Output= 1
Write DSS Sediment File= 0
DSS Sediment Output Type= 1
SV Curve= 0
Specific Gage Flag= 0
Subcell Erosion Methods= 0
Subcell Deposition Methods= 0
Advection Scheme= 1
Matrix Solver= 0
Implicit Weighting Factor= 1
Maximum Outer Loop Convergence Iterations= 5
Convergence Maximum Absolute= 0.001
Convergence RMSE= 0.0001
Grain Fractions Max Abs Error= 0.001
Max Subgrid Regions= 1
Max Subgrid Length Scale= 3.402823E+38
Initial Layer Thickness= 3.402823E+38
Min Layer Thickness= 3.402823E+38
Max Layer Thickness= 3.402823E+38
Number of Layers= 5

--- R-2829B_Basin15_Strm7_NC540.p01 (plan) ---

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Plan Title=Duplicate Effective
Program Version=6.41
Short Identifier=DE
Geom File=g01
Flow File=f01
Std Step Tol= 0.01
Critical Tol= 0.01
Num of Std Step Trials= 20
Max Error Tol= 0.3
Flow Tol Ratio= 0.001
Split Flow NTrial= 30
Split Flow Tol= 0.02
Split Flow Ratio= 0.02
Encroach Node=2964
       1     730     970
Encroach Node=2348
       1     620     770
Flow Ratio Tolerance=0.1
Flow Ratio Min Ratio=0.5
Flow Ratio Max Ratio=4
Flow Ratio Max Iterations= 10
Energy Slope Method= 0

--- R-2829B_Basin15_Strm7_NC540.p03 (plan) ---

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Plan Title=Corrected Effective
Short Identifier=CE
Geom File=g03
Flow File=f01
       1    4851    5115
Encroach Node=2973
       1    4943    5193
       1    4908    5162
       1    4958    5196
Encroach Node=2627
       1    4870    5120
Encroach Node=2557
       1    4842    5085
       1    4889    5150
       1    4940    5190
       1    4954    5180
       1    4956    5110
Encroach Node=2302
       1    4942    5095
Encroach Node=2284
       1    4936    5068
Encroach Node=2266
       1    4934    5073
Encroach Node=2202
       1    4945    5068
Encroach Node=2188
       1    4925    5065
Encroach Node=2174
       1    4896    5062
       1    4855    5056
Energy Slope Method= 0

--- R-2829B_Basin15_Strm7_NC540.f01 (steady flow) ---

Flow Title=FEMA
Program Version=6.20
Number of Profiles= 6
Profile Names=100-yr,FW,10-yr,25-yr,50-yr,500-yr
River Rch & RM=Basin15 Stream7,Main            ,19158
    1259    1259     535     802    1023    1864
River Rch & RM=Basin15 Stream7,Main            ,17606
    1649    1649     890    1212    1418    2589
River Rch & RM=Basin15 Stream7,Main            ,14624
    2423    2423    1208    1695    2039    3354
River Rch & RM=Basin15 Stream7,Main            ,11488
    2932    2932    1349    1968    2413    4232
River Rch & RM=Basin15 Stream7,Main            ,7623
    4211    4211    1717    2753    3449    6296
River Rch & RM=Basin15 Stream7,Main            ,4965
    4323    4323    1761    2801    3515    6480
Boundary for River Rch & Prof#=Basin15 Stream7,Main            , 1
Up Type= 0
Dn Type= 3
Dn Slope=0.0017
Boundary for River Rch & Prof#=Basin15 Stream7,Main            , 2
Up Type= 0
Dn Type= 3
Dn Slope=0.0017
Boundary for River Rch & Prof#=Basin15 Stream7,Main            , 3
Up Type= 0
Dn Type= 3
Dn Slope=0.0017
Boundary for River Rch & Prof#=Basin15 Stream7,Main            , 4
Up Type= 0
Dn Type= 3
Dn Slope=0.0017
Boundary for River Rch & Prof#=Basin15 Stream7,Main            , 5
Up Type= 0
Dn Type= 3
Dn Slope=0.0017
Boundary for River Rch & Prof#=Basin15 Stream7,Main            , 6
Up Type= 0
Dn Type= 3
Dn Slope=0.0017
DSS Import GetInterval= 0
DSS Import GetPeak= 0
DSS Import FillOption= 0

--- R-2829B_Basin15_Strm7_NC540.g04 (geometry) ---

Geom Title=Revised
Program Version=6.41

River Reach=Basin15 Stream7 ,Main
Reach XY= 30
2148236.45504248734502.8329701422148067.46598881734180.039403439
2147696.79443645734050.7162347442147666.58421922733773.801180065
 2147056.9146902733485.777359664 2146832.6689356 732783.06296593
2146481.21082097 732348.479224982145887.26102221731973.125740051
2146015.14074147731802.3950412872145892.99575484730910.740479946
 2146005.1303516730725.0726518032145990.81826121730459.544374883
2145793.08457649730279.8892915252145781.03239262729696.479863584
2146385.67035788728238.5575683122146344.18014038728028.696174204
2147011.85849512 726806.905140342146927.11492932725883.369684637
2147044.80716437725346.8271116022146611.29184937724589.399670601
2146853.56021231724225.9193218952146736.90710455723766.161485016
2147015.01624411722853.4059984682146805.85866994722785.073612332
2146851.01773602722537.8869739772146538.46894884721937.152897954
2145865.24272209721764.8348606822145489.70953846721292.447329938
2144989.39448494721374.4472351072144190.54909652721252.107574821

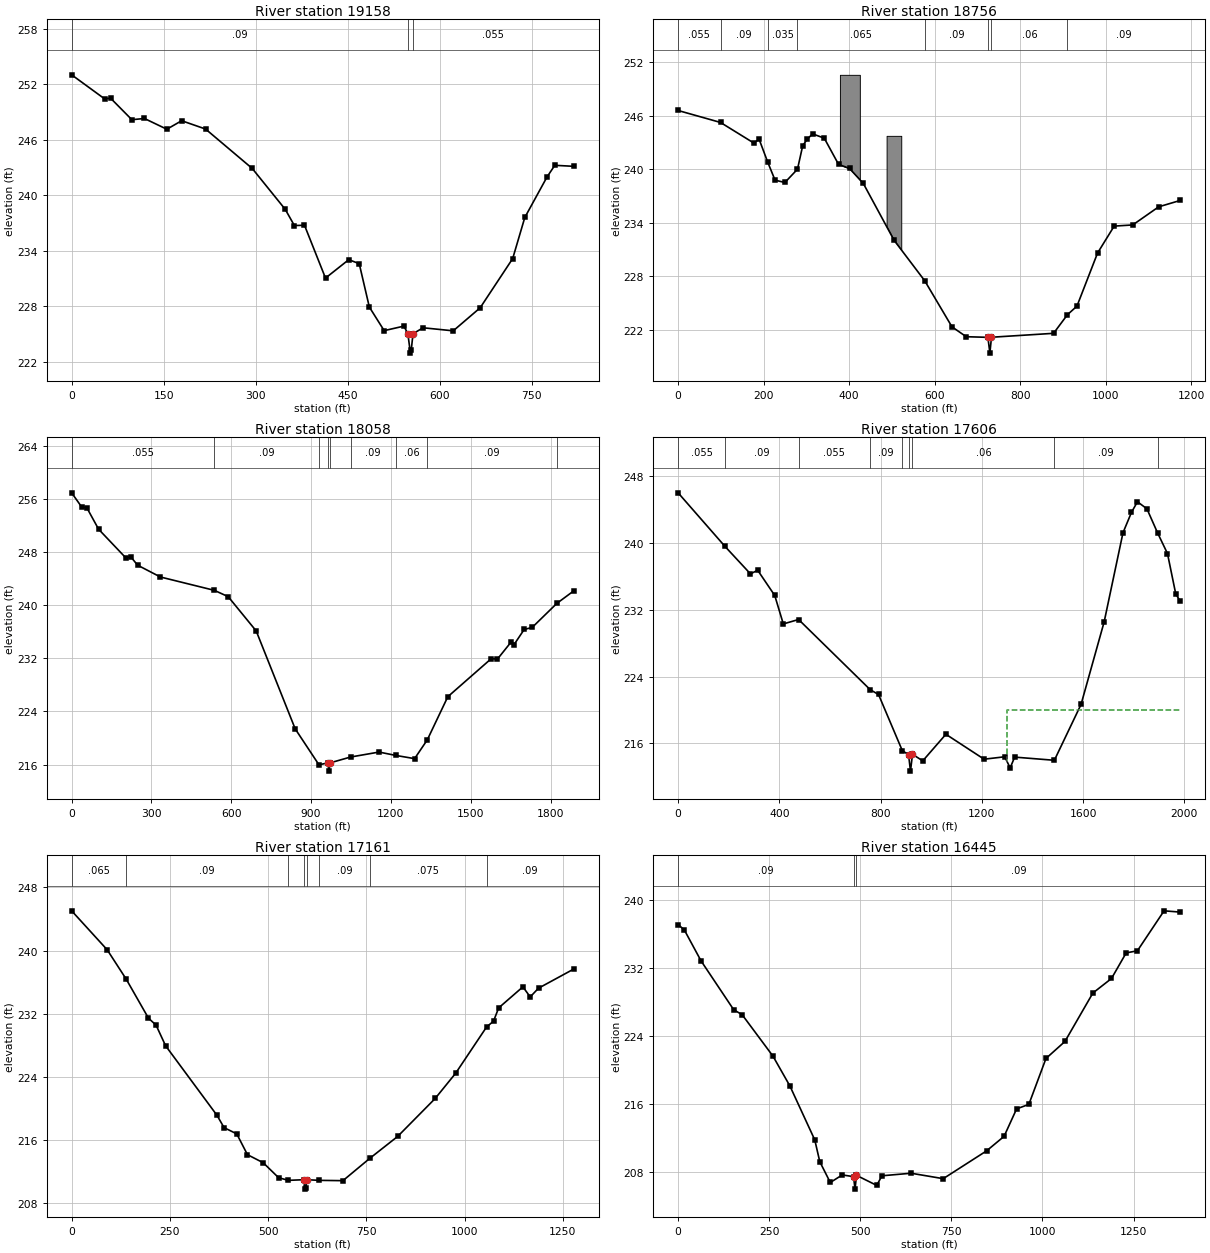
Type RM Length L Ch R = 1 ,19158   ,421.66,402.4,332.61
XS GIS Cut Line= 3
2148788.76617694734506.9484611152148236.45504248734502.832970142
 2147973.1912297734542.341293216
#Sta/Elev= 30
       0  253.01   53.78  250.41   63.39  250.49   98.13  248.16  118.63  248.29
  155.17  247.13   179.3  248.05  218.27  247.15  294.34  242.89  348.14  238.47
  363.02  236.72  379.53  236.75  413.76  231.04  451.67  233.03  468.74   232.6
  485.21  227.91  509.39  225.36  541.56  225.85     548  225.03  552.18  222.93
  553.52  223.24  556.37  225.03  572.87  225.67  621.96  225.34  665.87  227.83
  718.87  233.15  738.61  237.59  774.91  241.98  787.53  243.23  818.54  243.12
#Mann= 3 ,0,0
       0     .09       0     548     .05       0  556.37    .055       0
Bank Sta=548,556.37
XS Rating Curve= 0 ,0
Exp/Cntr=0.3,0.1

Type RM Length L Ch R = 1 ,18756   ,570.34,697.92,575.05
XS GIS Cut Line= 3
2148731.82968372733900.6528404362148116.30171645734126.859654844
 2147748.5235737734493.099290192
#Sta/Elev= 30
       0  246.58   99.15  245.24  177.22  242.93  189.49  243.36  209.12  240.85
  226.74  238.77  249.78  238.51  279.25     240  291.46  242.63   301.7  243.34
  314.46  243.96  341.86  243.48  375.35  240.54  400.96  240.08  433.26   238.4
  505.12  232.04  576.95  227.49  640.63  222.33  674.01  221.22  724.74  221.15
  729.32  219.38  733.08  221.16  878.31   221.6  910.83  223.69  933.05  224.65
  981.23   230.6 1020.09  233.62 1063.52  233.75 1124.15  235.78 1174.81   236.5
#Mann= 8 ,-1,0
       0    .055       0   99.15     .09       0  209.12    .035       0
  279.25    .065       0  576.95     .09       0  724.74     .05       0
  733.08     .06       0  910.83     .09       0
#Block Obstruct= 2 ,-1
  378.51   425.1 250.579  487.71     522 243.739
Bank Sta=724.74,733.08
XS Rating Curve= 0 ,0
Exp/Cntr=0.3,0.1

Type RM Length L Ch R = 1 ,18058   ,440.79,452.07,442.89
XS GIS Cut Line= 4
2148430.07649159733181.8795025352147744.82086885733696.422656834
2147369.73302549734107.5765513782147333.20145053734580.350824893
#Sta/Elev= 30
       0  256.91   37.09  254.81   57.79  254.61  101.33  251.43   203.6  247.12
  222.84  247.25  247.91  246.02  333.64  244.24  536.47  242.23   588.4  241.28
  693.68  236.12  840.16  221.39  929.48  215.98  963.31  216.25  967.09  215.02
   971.2  216.26 1048.21  217.14 1155.59  217.89 1217.35  217.39 1289.07   216.9
 1336.84  219.73 1413.96  226.22 1577.23  231.95 1600.62  231.89 1652.87   234.5
 1662.48  234.04 1700.92  236.34 1731.12  236.65 1823.85  240.27 1887.66  242.16
#Mann= 9 ,-1,0
       0    .055       0  536.47     .09       0  929.48    .075       0
  963.31     .05       0   971.2    .075       0 1048.21     .09       0
 1217.35     .06       0 1336.84     .09       0 1823.85    .035       0
Bank Sta=963.31,971.2
XS Rating Curve= 0 ,0
Exp/Cntr=0.3,0.1

Type RM Length L Ch R = 1 ,17606   ,377.58,444.65,428.51
XS GIS Cut Line= 5
2147990.63372362733030.8974311352147526.01946414733241.989370763
2147271.15200824733588.2245034582146862.40321165733946.481219113
2146475.29313421734263.862989962
#Sta/Elev= 30
       0  246.04  185.34  239.61  285.89  236.32  314.31  236.76  381.82  233.73
  415.63  230.32  476.05  230.85  759.22  222.43  791.89  221.86  885.82  215.13
  910.62  214.64  918.18  212.67   926.1  214.69  966.68   213.9 1058.09  217.09
  1209.1   214.1  1290.6  214.39 1312.01  213.06 1329.86  214.35 1486.68  213.97
 1592.18  220.67  1683.4  230.56 1757.84  241.25 1791.44   243.7 1815.03  244.97
 1852.51  244.12 1894.67  241.23 1933.65  238.76 1966.25  233.93 1984.36  233.02
#Mann= 9 ,-1,0
       0    .055       0  185.34     .09       0  476.05    .055       0
  759.22     .09       0  885.82     .06       0  910.62     .05       0
   926.1     .06       0 1486.68     .09       0 1894.67    .035       0
#XS Ineff= 2 , 0
       0                    1300       0     220
Permanent Ineff=
       F       F
Bank Sta=910.62,926.1
XS Rating Curve= 0 ,0
Exp/Cntr=0.3,0.1

Type RM Length L Ch R = 1 ,17161   ,677.46,716.26,573.94
XS GIS Cut Line= 4
 2147417.8213107732881.3282082682147114.86556965733241.989370763
 2146780.6533221733427.1291711932146357.47719353733465.599669099
#Sta/Elev= 30
       0  245.02   90.44  240.09  138.79  236.38  195.48  231.44  214.81  230.56
  239.06  227.95  370.11  219.13  387.87  217.59  420.17   216.8  447.36  214.17
  487.48  213.15  526.58  211.26  551.46  210.92  590.31     211   594.6  209.81
  596.05  209.94  598.48     211  630.06  210.92  690.37  210.88  759.14  213.72
  829.74  216.48  925.16  221.28  977.36  224.48 1055.89  230.32 1073.58  231.06
 1086.73  232.74 1148.34   235.4 1166.98  234.13 1188.08  235.23 1278.01  237.66
#Mann= 8 ,-1,0
       0    .065       0  138.79     .09       0  551.46     .06       0
  590.31     .05       0  598.48     .06       0  630.06     .09       0
  759.14    .075       0 1055.89     .09       0
Bank Sta=590.31,598.48
XS Rating Curve= 0 ,0
Exp/Cntr=0.3,0.1

Type RM Length L Ch R = 1 ,16445   ,442.74,474.29,536.38
XS GIS Cut Line= 4
2147064.37348866732383.6161816722146807.10158598 732638.48298651
2146446.44042355733044.8279873732146299.77177215733494.452379823
#Sta/Elev= 30
       0  237.06   17.05  236.42   62.97  232.78  152.62  227.03  175.75  226.45
  260.26  221.58  306.79  218.07  375.09  211.72  388.84  209.16  417.66  206.71
  450.56   207.6  481.46   207.4  485.59  205.93  489.61  207.55  545.12  206.37
   559.5   207.5  639.45   207.8  727.68  207.16  846.65  210.43   894.7  212.14
  929.06  215.37   962.7   215.9 1009.67   221.3 1061.72   223.3 1138.42     229
  1189.5  230.71 1229.81  233.72 1260.65  233.97 1333.82  238.67  1378.4  238.52
#Mann= 3 ,0,0
       0     .09       0  481.46     .05       0  489.61     .09       0
Bank Sta=481.46,489.61
XS Rating Curve= 0 ,0
Exp/Cntr=0.3,0.1

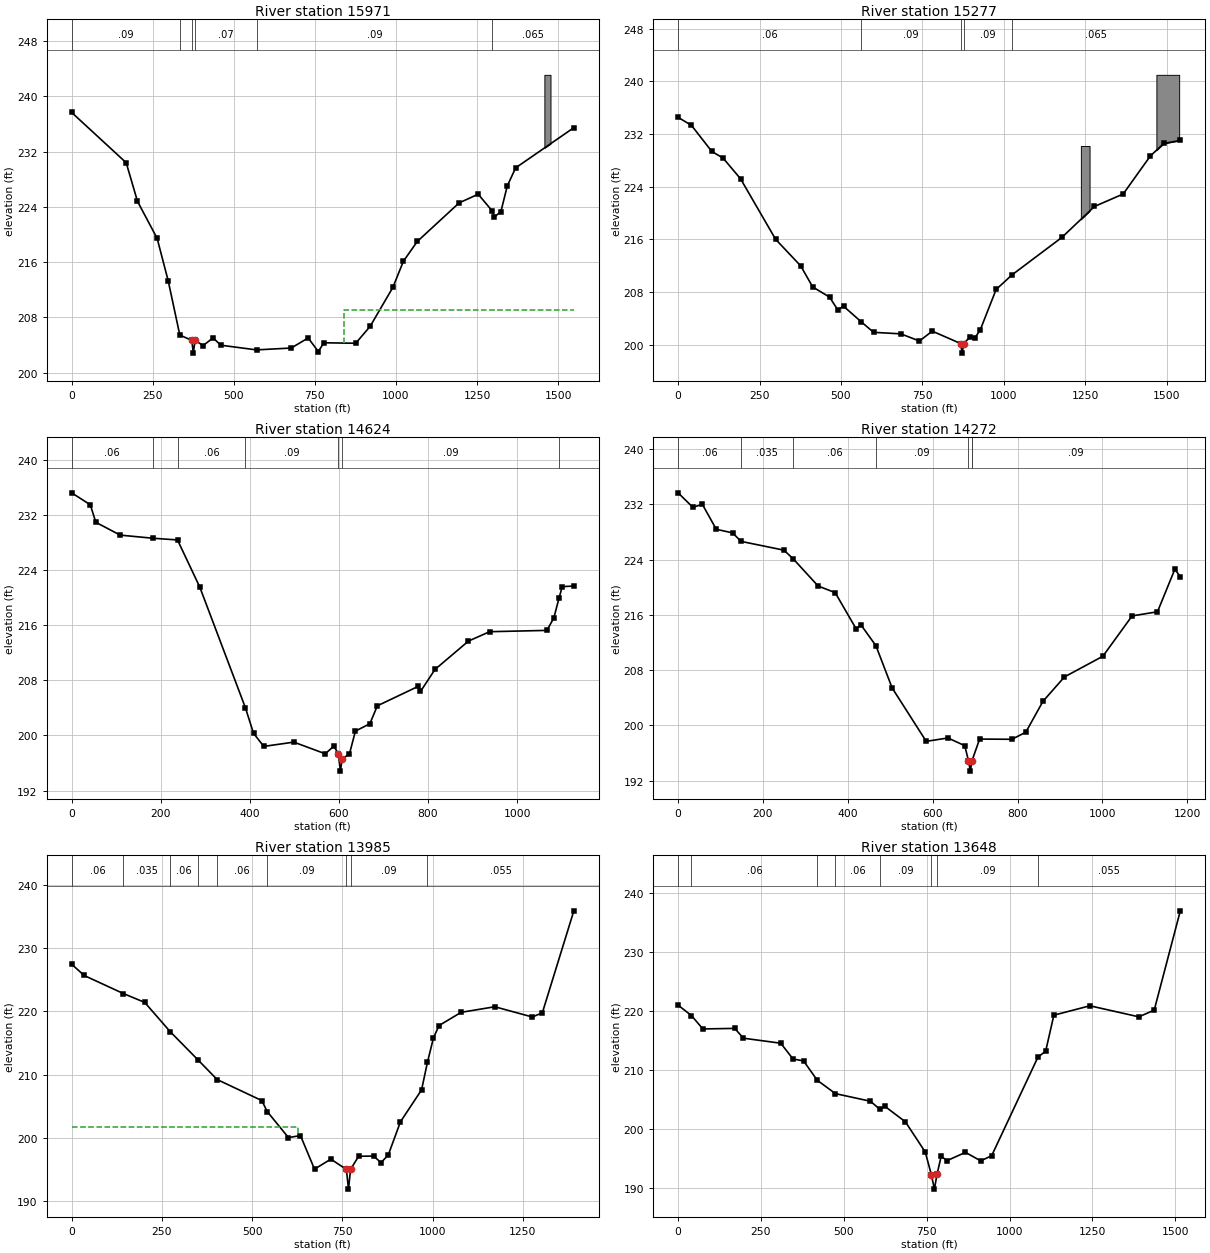
Type RM Length L Ch R = 1 ,15971   ,529.12,693.76,578.46
XS GIS Cut Line= 2
2146809.50603282732174.4325641992145431.78014475732881.328208268
#Sta/Elev= 30
       0  237.69   168.2   230.4  202.96  224.81  263.63  219.44  298.01  213.23
  333.55  205.42  370.44  204.67  375.14  202.81  380.62  204.66  405.43  203.91
  436.23  205.02  459.63  203.96     570  203.28  677.12  203.55  729.29  205.01
  760.54  203.04  777.75  204.31  875.85  204.24  920.25  206.68  990.66  212.35
 1022.87  216.12 1065.71  218.99 1194.71  224.58 1253.53  225.84 1297.48  223.38
 1303.42  222.54 1323.52  223.31  1343.4  227.06 1369.12  229.66 1548.49  235.48
#Mann= 6 ,-1,0
       0     .09       0  333.55     .07       0  370.44     .05       0
  380.62     .07       0     570     .09       0 1297.48    .065       0
#XS Ineff= 2 , 0
       0                     840       0     209
Permanent Ineff=
       F       F
#Block Obstruct= 1 ,-1
 1457.64 1476.53  243.14
Bank Sta=370.44,380.62
XS Rating Curve= 0 ,0
Exp/Cntr=0.3,0.1

Type RM Length L Ch R = 1 ,15277   ,530.99,653.18,591.23
XS GIS Cut Line= 4
2146739.77837735731763.2786697152145886.21343082732013.337231994
2145749.16256672732244.1602196692145393.30964679732388.425075352
#Sta/Elev= 30
       0  234.55   40.92  233.34  103.47  229.37   138.2  228.36  191.92   225.2
  299.25  216.03   376.3  211.99  413.28  208.78  464.96  207.24  490.17   205.3
  507.87  205.86  561.86   203.5   600.2  201.89  683.71  201.66   740.9  200.57
  780.32  202.07  867.44  200.19  872.07  198.73  876.85  200.19  897.65  201.24
  911.44  201.09  927.05  202.19  976.39   208.4 1025.19  210.62 1178.27  216.31
 1278.29  221.01 1366.55  222.91 1449.99  228.69 1490.93  230.58 1541.87  231.05
#Mann= 5 ,-1,0
       0     .06       0  561.86     .09       0  867.44     .05       0
  876.85     .09       0 1025.19    .065       0
#Block Obstruct= 2 ,-1
 1236.53 1263.28 230.205 1468.46 1538.38 241.013
Bank Sta=867.44,876.85
XS Rating Curve= 0 ,0
Exp/Cntr=0.3,0.1

Type RM Length L Ch R = 1 ,14624   ,300.01,351.83,317.72
XS GIS Cut Line= 4
2146571.46970463731330.4854049682146350.26385307731306.441587925
2145931.89726925731455.514686108 2145472.6550895731491.580737233
#Sta/Elev= 30
       0  235.22    41.8  233.49   54.26  230.94  109.03  229.08  182.06  228.63
  237.63  228.38  287.73  221.52  389.93  204.04   408.3  200.31  431.33  198.41
  498.74  199.03  569.18  197.34  588.82  198.46  598.59  197.32  603.27  194.82
  607.28  196.61  623.59  197.31  636.94  200.63   669.4   201.7   686.2   204.3
  777.49  207.11  783.07  206.38  815.59  209.58  890.79   213.7  938.24  215.06
 1066.78  215.25 1082.27  217.04 1094.38  220.01 1101.21   221.6  1127.3  221.69
#Mann= 7 ,-1,0
       0     .06       0  182.06    .035       0  237.63     .06       0
  389.93     .09       0  598.59     .05       0  607.28     .09       0
 1094.38    .065       0
Bank Sta=598.59,607.28
XS Rating Curve= 0 ,0
Exp/Cntr=0.3,0.1

Type RM Length L Ch R = 1 ,14272   ,272.64,286.43,311.36
XS GIS Cut Line= 4
2146571.46970463731318.4631708862146054.52210355731116.493544936
2145903.04195422731121.9554740792145491.89066404731364.147009313
#Sta/Elev= 30
       0  233.68   34.58  231.59   57.25     232   89.95   228.4  128.45  227.88
  148.33  226.65  249.31  225.38   271.2  224.13  329.97  220.19  370.23  219.23
  419.43  214.01  431.41  214.53  466.28  211.54  504.51  205.43  584.84   197.7
  636.06  198.19   675.8  197.07  684.45  194.87  688.94  193.39  692.48  194.86
   710.7  198.03  786.73     198  819.53  199.02  859.94  203.49  910.72  207.03
 1001.21  210.02 1070.11  215.86 1129.97  216.46 1170.91  222.62 1183.76  221.53
#Mann= 7 ,-1,0
       0     .06       0  148.33    .035       0   271.2     .06       0
  466.28     .09       0  684.45     .05       0  692.48    .055       0
   692.5     .09       0
Bank Sta=684.45,692.48
XS Rating Curve= 0 ,0
Exp/Cntr=0.3,0.1

Type RM Length L Ch R = 1 ,13985   ,287.4,337.57,270.47
XS GIS Cut Line= 3
 2146658.0284878730998.6776042582145999.22047788730849.603855014
2145287.51594019730775.067305923
#Sta/Elev= 30
       0  227.44   34.74  225.66  143.14  222.81  202.35  221.41   273.2  216.77
  349.99  212.32  402.99  209.22  526.82  205.89  541.68  204.16  600.48  200.05
  633.82  200.36  672.74  195.06  717.98  196.64  761.07  195.01  766.85   191.9
  772.58  195.02  794.84  197.09  836.12  197.13   857.2  196.09  877.17  197.32
  910.77  202.54  969.32  207.59  985.43  211.93  1002.1  215.78  1017.6  217.75
 1078.85  219.84 1172.14  220.72 1276.16   219.1 1303.85  219.77 1391.06  235.88
#Mann= 9 ,-1,0
       0     .06       0  143.14    .035       0   273.2     .06       0
  349.99    .035       0  402.99     .06       0  541.68     .09       0
  761.07     .05       0  772.58     .09       0  985.43    .055       0
#XS Ineff= 2 , 0
          626.82  201.66
Permanent Ineff=
       F       F
Bank Sta=761.07,772.58
XS Rating Curve= 0 ,0
Exp/Cntr=0.3,0.1

Type RM Length L Ch R = 1 ,13648   ,316.68,338.04,242.55
XS GIS Cut Line= 3
2146660.43293464730919.3315104842145993.31385952730558.225007713
2145239.42765498730618.780867279
#Sta/Elev= 30
       0     221   40.14  219.24   74.58  216.97  170.74  217.06   197.1   215.4
  309.62  214.55  346.72  211.87   378.4  211.56  419.63  208.28  474.47  206.01
  580.09  204.72  608.53  203.36  624.13  203.84  685.69  201.23  745.56  196.11
  763.89  192.27  773.14  189.83  780.93  192.32  793.57  195.41     811  194.65
  866.86  196.06  912.76  194.62  945.83  195.49 1085.73  212.23 1108.58  213.17
 1133.44   219.3 1242.18  220.89 1389.95  219.02 1436.23  220.16  1514.9  236.98
#Mann= 8 ,-1,0
       0    .035       0   40.14     .06       0  419.63    .035       0
  474.47     .06       0  608.53     .09       0  763.89     .05       0
  780.93     .09       0 1085.73    .055       0
Bank Sta=763.89,780.93
XS Rating Curve= 0 ,0
Exp/Cntr=0.3,0.1

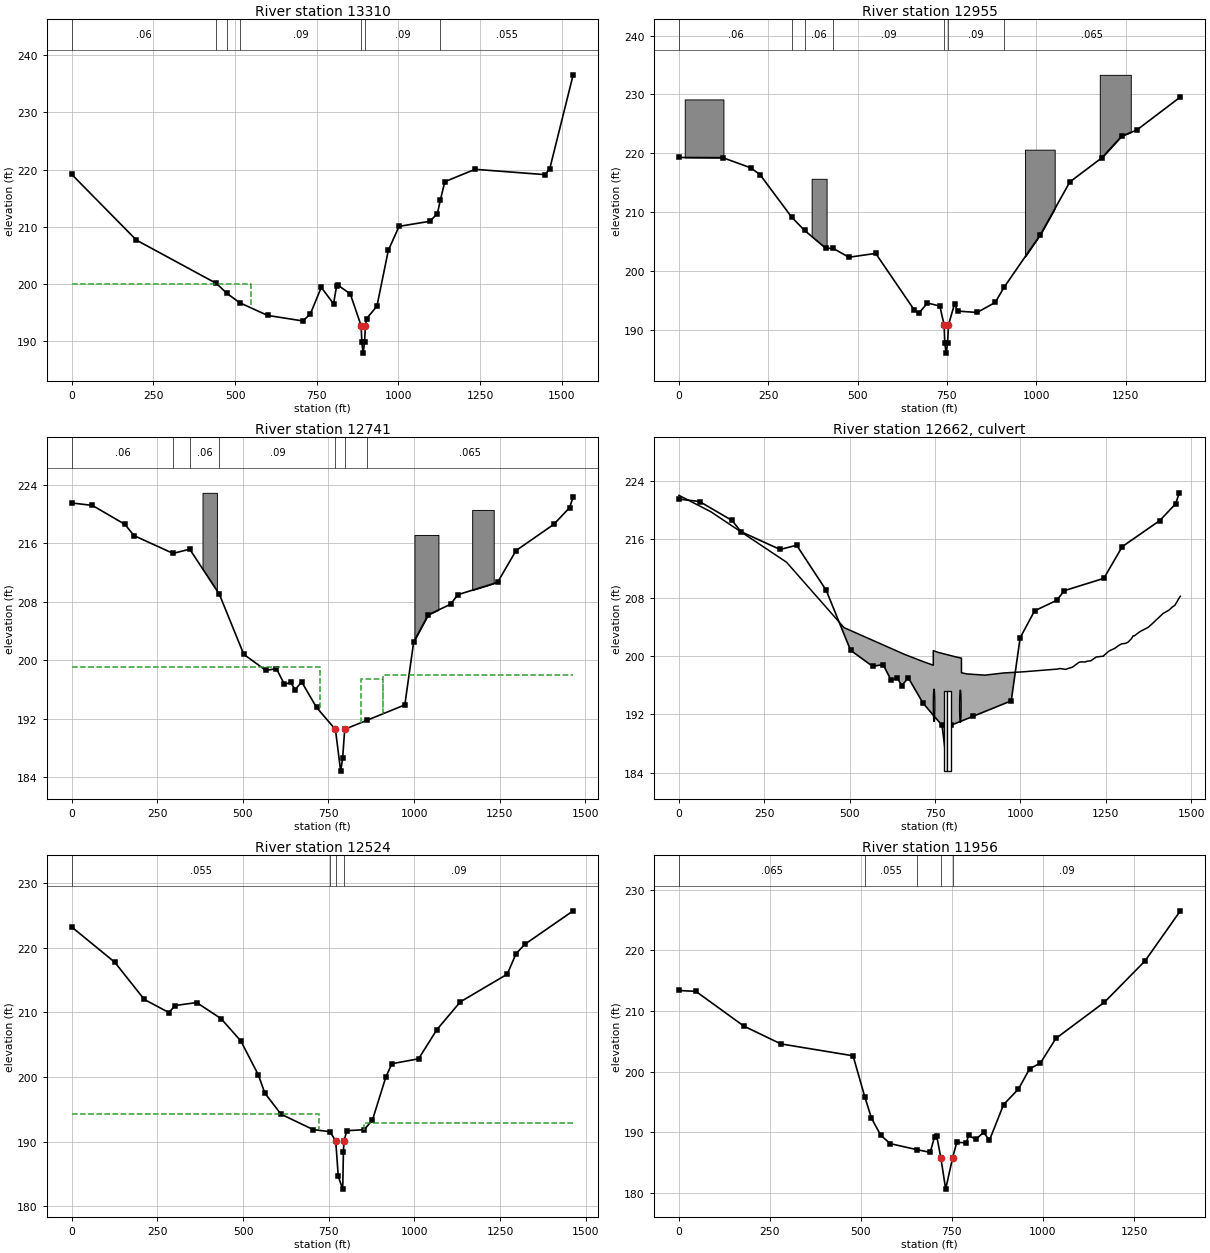
Type RM Length L Ch R = 1 ,13310   ,245.85,354.67,282.73
XS GIS Cut Line= 2
2146648.41070056729991.2306659222145227.40607196730570.692582071
#Sta/Elev= 30
       0  219.15  198.08  207.67  443.04   200.1  474.19  198.41  513.79  196.75
  599.14  194.53  707.02  193.56  730.02  194.74  763.63  199.42  801.35  196.56
  810.56  199.67  814.31  199.82  852.48  198.29  885.73   192.7  887.93   189.8
  891.67  187.94  896.21   189.8  898.78  192.73  902.18  193.96  934.08  196.14
   968.9  205.89 1001.81  210.08 1095.93  210.96 1119.15  212.31 1128.25   214.7
 1141.85  217.88  1234.4  220.04 1448.64  219.11 1463.12  220.17 1534.61  236.54
#Mann= 7 ,-1,0
       0     .06       0  443.04    .035       0  474.19     .06       0
  513.79     .09       0  885.73     .05       0  898.78     .09       0
 1128.25    .055       0
#XS Ineff= 2 , 0
       0     550     200               0
Permanent Ineff=
       F       F
Bank Sta=885.73,898.78
XS Rating Curve= 0 ,0
Exp/Cntr=0.3,0.1

Type RM Length L Ch R = 1 ,12955   ,199.98,214.36,195.97
XS GIS Cut Line= 3
2146577.14583987729781.6987194422145883.36624807730037.279761493
2145231.84319764730164.695910215
#Sta/Elev= 30
       0  219.29  122.95  219.25  200.84  217.53  226.83  216.38  315.73  209.12
  351.79  206.87  410.95  203.85  432.19  203.81  475.62  202.32  550.72  202.97
  658.56  193.35  670.93  192.78  695.62  194.53  730.14  194.02  742.18  190.78
  743.98  187.69  747.89  186.01  751.99  187.69  754.06  190.75  771.28  194.39
  779.97  193.16  834.55  192.93  885.17  194.63  910.13  197.23 1011.78  206.18
 1094.02  215.13  1183.9  219.25 1239.37  222.94 1281.27  223.95 1403.22  229.57
#Mann= 7 ,-1,0
       0     .06       0  315.73    .035       0  351.79     .06       0
  432.19     .09       0  742.18     .05       0  754.06     .09       0
  910.13    .065       0
#Block Obstruct= 4 ,-1
   16.25  124.54 229.164  371.37  413.26 215.662   968.4 1051.58 220.616
 1177.72 1264.52 233.346
Bank Sta=742.18,754.06
XS Rating Curve= 0 ,0
Exp/Cntr=0.5,0.3

Type RM Length L Ch R = 1 ,12741   ,152.2,216.57,231.48
BEGIN DESCRIPTION:
Surveyed Section
END DESCRIPTION:
XS GIS Cut Line= 6
 2146576.6744563729705.3039816022145914.78487396729819.305882335
 2145772.0018816729861.7538418772145671.31982189729870.150198758
2145566.84716117  729927.64792492145148.56326479729993.935912788
#Sta/Elev= 30
       0   221.5    60.3  221.17  155.56  218.57  181.74  217.04  296.04   214.6
  344.68  215.18   431.4  208.99   502.5  200.79  567.07  198.59  597.86  198.82
  621.43  196.68  639.57  196.94  652.54  195.95 671.709  197.01 715.118  193.52
   770.4   190.5  785.61   184.8 791.311  186.53 797.513  190.53  862.43  191.76
  973.03  193.86     999  202.49 1041.34  206.19 1106.59  207.64 1128.06  208.95
 1244.07  210.64 1298.09  214.99 1407.86  218.56 1454.52  220.86 1464.84  222.36
#Mann= 7 ,-1,0
       0     .06       0  296.04    .035       0  344.68     .06       0
   431.4     .09       0   770.4     .05       0 797.513     .09       0
  862.43    .065       0
#XS Ineff= 3 ,-1
       0  724.75  199.07  846.25     910  197.38     910 1464.84     198
Permanent Ineff=
       F       F       F
#Block Obstruct= 3 ,-1
  382.04   424.1 222.891 1001.14 1071.29 217.126 1169.83 1232.72 220.552
Bank Sta=770.4,797.513
XS Rating Curve= 0 ,0
Exp/Cntr=0.5,0.3

Type RM Length L Ch R = 2 ,12662   ,,,
BEGIN DESCRIPTION:
Poole Road
deck includes 2' tall guardrail (see STR_120PHT1.JPG)
END DESCRIPTION:
Bridge Culvert--1,0,-1,-1, 0
Deck Dist Width WeirC Skew NumUp NumDn MinLoCord MaxHiCord MaxSubmerge Is_Ogee
57,41,2.6,0, 60, 60, , , 0.98, 0, 1,1,,
       0   93.71  315.15   483.5 660.432 714.846  744.75  744.75 758.908 810.069
  827.25  827.25 842.475 896.069 950.7961008.932 1110.24 1112.37    1115 1132.08
 1140.12 1151.73 1168.93 1171.51 1177.13 1189.07 1195.01 1205.81 1219.85 1222.29
 1227.09 1240.15 1242.52 1244.94 1258.93 1264.48 1270.55 1277.78 1286.37 1296.32
 1296.82 1308.15 1315.05 1325.04 1330.19 1333.23 1346.79 1351.95 1354.23 1373.55
 1385.25 1395.32 1416.74 1417.29  1418.6 1434.88 1443.96 1452.09 1466.39 1468.14
  222.02  219.76  212.85  203.89  200.23  199.24  198.74  200.74   200.5  199.89
  199.71  197.71  197.55  197.38  197.68  197.84  198.22  198.26  198.29  198.17
   198.3  198.46  199.06  199.14   199.2  199.18  199.29  199.34   199.8  199.88
  199.89  199.97  199.96   200.1  200.67   200.8  200.93   201.1  201.41  201.67
  201.68  201.74   201.9  202.38  202.78  202.75  203.24   203.4  203.45  203.92
   204.4  204.85  205.79  205.81  205.86  206.29  206.69  206.95  208.08  208.19
                                                                                
                                                                                
                                                                                
                                                                                
                                                                                
                                                                                
       0   93.71  315.15   483.5 660.432 714.846  744.75  744.75 758.908 810.069
  827.25  827.25 842.475 896.069 950.7961008.932 1110.24 1112.37    1115 1132.08
 1140.12 1151.73 1168.93 1171.51 1177.13 1189.07 1195.01 1205.81 1219.85 1222.29
 1227.09 1240.15 1242.52 1244.94 1258.93 1264.48 1270.55 1277.78 1286.37 1296.32
 1296.82 1308.15 1315.05 1325.04 1330.19 1333.23 1346.79 1351.95 1354.23 1373.55
 1385.25 1395.32 1416.74 1417.29  1418.6 1434.88 1443.96 1452.09 1466.39 1468.14
  222.02  219.76  212.85  203.89  200.23  199.24  198.74  200.74   200.5  199.89
  199.71  197.71  197.55  197.38  197.68  197.84  198.22  198.26  198.29  198.17
   198.3  198.46  199.06  199.14   199.2  199.18  199.29  199.34   199.8  199.88
  199.89  199.97  199.96   200.1  200.67   200.8  200.93   201.1  201.41  201.67
  201.68  201.74   201.9  202.38  202.78  202.75  203.24   203.4  203.45  203.92
   204.4  204.85  205.79  205.81  205.86  206.29  206.69  206.95  208.08  208.19
                                                                                
                                                                                
                                                                                
                                                                                
                                                                                
                                                                                
BR Coef=-1 , 1 , 0 ,1.25, 0 ,,,0.8,0,2,0,
WSPro=,,,, 1 ,,,, 0 ,,,, 0 ,,,,-1 ,-1 ,-1 , 0 , 0 , 0 , 0 , 0
Culvert=1,4.5,4.5,68.3,0.012,0.2,1,1,2,191.01,747,189.84,748,Culvert #1  , 0 ,49
     747     748
BC Culvert Barrel=1,,0
Culvert Bottom n=0.012
Culvert=2,11,10,52.3,0.012,0.4,1,8,1,184.23,780,183.21,781,Culvert #2  , 0 ,52
     780     781
BC Culvert Barrel=1,,0
Culvert Bottom n=0.05
Culvert Bottom Depth=3
Culvert Depth Blocked=3
Culvert=2,11,10,52.3,0.012,0.4,1,8,1,184.23,791,183.21,792,Culvert #3  , 0 ,52
     791     792
BC Culvert Barrel=1,,0
Culvert Bottom n=0.05
Culvert Bottom Depth=1
Culvert Depth Blocked=1
Culvert=1,4.5,4.5,61,0.012,0.2,1,1,2,190.86,824,189.77,825,Culvert #4  , 0 ,49
     824     825
BC Culvert Barrel=1,,0
Culvert Bottom n=0.012
BC Design=,, 0 ,, 0 ,,,,,,
BC Use User HTab Curves=0
BC User HTab FreeFlow(D)= 0

Type RM Length L Ch R = 1 ,12524   ,550.9,567.72,532.11
BEGIN DESCRIPTION:
Surveyed Section
END DESCRIPTION:
XS GIS Cut Line= 6
2146580.59918022729615.0262165072146234.85235924729664.231107771
 2145879.9578324729683.2290372852145744.59392244729628.180682659
 2145595.2799238729625.7606098652145139.59851301 729691.94442451
#Sta/Elev= 30
       0  223.25  125.55  217.79  211.74  212.02  283.59  209.99  301.57  211.08
  364.46  211.54  435.68  209.05  493.54  205.57  544.37  200.33  563.53  197.49
  610.46  194.24 704.664  191.84 752.928  191.53  770.18  190.11 777.665  184.58
 790.602  182.62 792.649  188.43  794.42  190.11 802.759  191.68 853.177  191.83
  877.36  193.33   916.3  199.97  933.95  202.06 1011.92  202.82 1065.45  207.35
 1133.77  211.65 1270.59  215.94 1296.28  219.11  1322.2  220.58 1462.94  225.76
#Mann= 4 ,-1,0
       0    .055       0 752.928     .09       0  770.18     .05       0
  794.42     .09       0
#XS Ineff= 2 , 0
       0  720.75  194.34  852.25       0   192.8
Permanent Ineff=
       F       F
Bank Sta=770.18,794.42
XS Rating Curve= 0 ,0
Exp/Cntr=0.5,0.3

Type RM Length L Ch R = 1 ,11956   ,372.97,468.24,433.05
XS GIS Cut Line= 3
2146588.30018127729411.7680987122146374.30832124729243.459426045
2145304.34706789728966.952599883
#Sta/Elev= 30
       0  213.36   46.47  213.22  178.32  207.49  280.07  204.55  478.36  202.59
  510.59  195.81  528.88   192.3   554.7  189.45  580.71   188.1  654.25   187.1
  690.31  186.67  702.26  189.25  708.07  189.38  719.58  185.73  732.72   180.6
  751.96  185.81  763.02   188.3  789.42  188.26  795.86  189.47  815.43  188.81
  836.91  189.96  852.97  188.66  891.79  194.54  932.73  197.12  963.38  200.45
  992.77  201.38  1035.6  205.46 1168.88  211.43 1280.31  218.23 1377.36   226.5
#Mann= 5 ,-1,0
       0    .065       0  510.59    .055       0  654.25     .09       0
  719.58     .05       0  751.96     .09       0
Bank Sta=719.58,751.96
XS Rating Curve= 0 ,0
Exp/Cntr=0.3,0.1

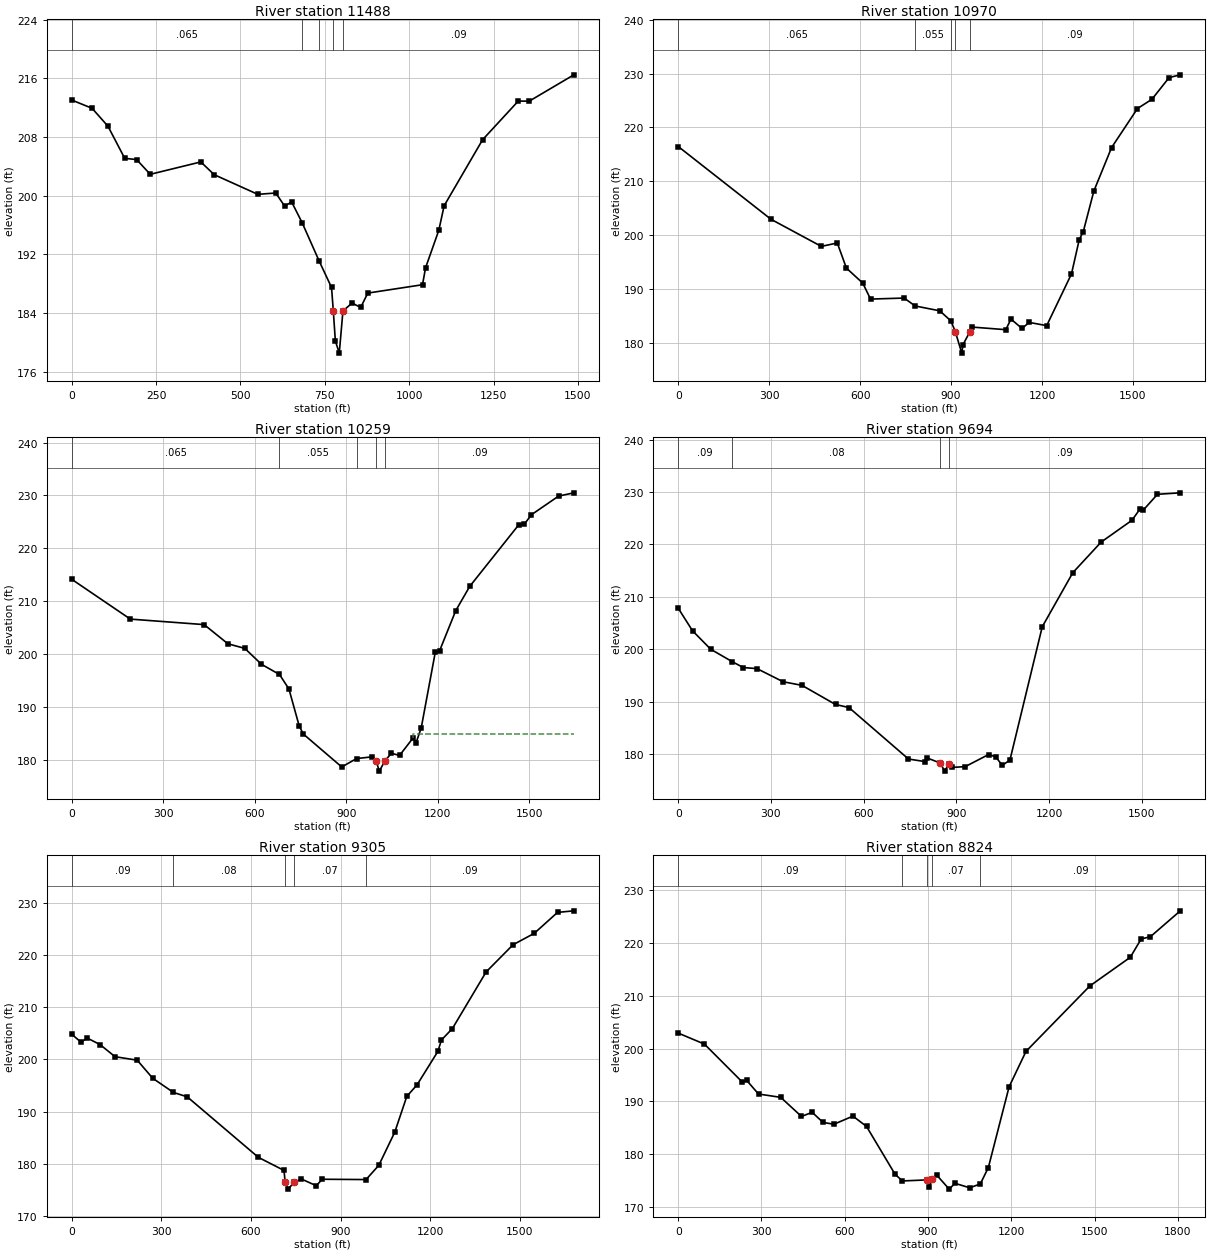
Type RM Length L Ch R = 1 ,11488   ,518.93,517.8,471.54
XS GIS Cut Line= 4
2146595.51352173729399.7465157512146129.80479288728787.345696628
2145857.36072016 728555.799356522145503.91289812728481.262807429
#Sta/Elev= 30
       0  213.06   60.27  211.93  107.12   209.5  156.93  205.11  192.24  204.94
  232.57  202.93  382.45  204.62  422.16  202.88   551.3   200.2  604.61  200.38
  631.14  198.58  651.59  199.17  682.61  196.35  732.76  191.15  769.91   187.5
  775.17  184.31  781.24  180.21  792.85  178.54  803.74  184.29  830.87  185.37
  856.32  184.77  877.38  186.73 1039.58  187.87 1048.57  190.17 1087.91   195.3
 1103.67  198.64 1217.73  207.65 1323.37  212.92 1355.96  212.91 1488.13   216.5
#Mann= 5 ,-1,0
       0    .065       0  682.61    .055       0  732.76     .09       0
  775.17     .05       0  803.74     .09       0
Bank Sta=775.17,803.74
XS Rating Curve= 0 ,0
Exp/Cntr=0.3,0.1

Type RM Length L Ch R = 1 ,10970   ,602.89,711.56,591.48
XS GIS Cut Line= 4
2147078.79951847728882.798914671 2146682.0723049 728493.28439039
2146316.60224879728315.3585814832145672.22091973728058.086678803
#Sta/Elev= 30
       0  216.46  305.96  202.93  471.98  197.89   524.7  198.52  554.81  193.85
  608.65  191.06  634.45  188.09  745.28  188.28  781.44  186.81  862.66  185.91
  899.37  184.04  914.15  182.02  935.38  178.04  939.62  179.64  962.46  182.05
  970.15  182.88 1080.74   182.4 1097.53  184.37  1133.8  182.64 1158.15  183.75
  1215.5  183.15 1297.26  192.77 1322.96  199.16 1336.27  200.65 1371.15  208.19
 1429.62  216.27 1514.95  223.52 1562.78  225.25 1619.38  229.28  1656.3  229.79
#Mann= 5 ,-1,0
       0    .065       0  781.44    .055       0  899.37     .09       0
  914.15     .05       0  962.46     .09       0
Bank Sta=914.15,962.46
XS Rating Curve= 0 ,0
Exp/Cntr=0.3,0.1

Type RM Length L Ch R = 1 ,10259   ,499.4,564.97,465.07
XS GIS Cut Line= 6
2147480.33562571727904.2046869992147122.07891005727824.859244287
2146840.76319033727863.3297422532146520.97697264727769.557618618
2146215.61743581727622.8889672762145999.22047788727382.448192298
#Sta/Elev= 30
       0  214.13  192.06   206.6  434.03  205.56  511.99  201.93  567.38  201.06
  622.04  198.05   681.1  196.12  712.05  193.38  745.51  186.43  759.09  184.86
  885.24  178.62  933.98  180.21  986.01  180.54  997.84  179.78 1008.45  177.83
    1027  179.78  1048.1  181.21 1074.82   180.8 1119.74  184.15 1128.62  183.15
  1145.8  185.97 1191.97  200.33 1206.35  200.64 1259.07   208.2  1304.8  212.78
  1466.3  224.49 1484.34   224.6 1507.41  226.36 1596.25  229.88 1646.36   230.5
#Mann= 5 ,-1,0
       0    .065       0   681.1    .055       0  933.98     .09       0
  997.84     .05       0    1027     .09       0
#XS Ineff= 2 , 0
                         1119.76          184.81
Permanent Ineff=
       F       F
Bank Sta=997.84,1027
XS Rating Curve= 0 ,0
Exp/Cntr=0.3,0.1

Type RM Length L Ch R = 1 ,9694    ,345.57,388.88,347.19
XS GIS Cut Line= 4
2147605.36490685727413.705349803 2146795.0793519727346.382141113
2146407.96992558 727262.227804782146001.62492472727351.191034734
#Sta/Elev= 30
       0   207.8   46.34  203.49  105.21  199.97   175.2  197.59  210.58  196.48
  254.79  196.28  339.49  193.77  400.66  193.08  509.08  189.43  552.49  188.85
  745.23  179.02  798.83  178.53  806.09  179.22  848.93  178.23  862.04  176.71
  875.87  178.02  884.87  177.41  928.97  177.57 1004.42  179.87 1027.48  179.44
 1048.93  177.82  1073.7  178.82 1178.26  204.26 1277.27  214.59 1368.97  220.43
 1468.44  224.58 1495.89  226.83 1505.46  226.54 1551.27  229.55  1625.2  229.83
#Mann= 4 ,-1,0
       0     .09       0   175.2     .08       0  848.93     .05       0
  875.87     .09       0
Bank Sta=848.93,875.87
XS Rating Curve= 0 ,0
Exp/Cntr=0.3,0.1

Type RM Length L Ch R = 1 ,9305    ,426.16,480.94,403.14
XS GIS Cut Line= 4
2147662.77017933727178.9752173422146625.86958134726959.572863698
2146346.35670841726800.2810293442146048.81146097726767.220373929
#Sta/Elev= 30
       0  204.81   30.68  203.31   52.29  204.07   94.81  202.83  144.89  200.52
   219.1  199.85  271.05  196.39  340.39  193.68  386.58  192.84  624.72  181.26
  710.55  178.76  714.38  176.55  725.16  175.18  743.65  176.49  768.68  177.12
  818.72  175.83  838.35  177.07  985.21  177.01 1027.91  179.73 1081.31  186.07
  1121.7  192.93 1155.97  195.13 1225.78  201.54 1237.58  203.71 1274.38  205.91
 1387.32  216.74 1477.15  221.93 1548.33  224.12 1626.33  228.13 1680.95  228.43
#Mann= 5 ,-1,0
       0     .09       0  340.39     .08       0  714.38     .05       0
  743.65     .07       0  985.21     .09       0
Bank Sta=714.38,743.65
XS Rating Curve= 0 ,0
Exp/Cntr=0.3,0.1

Type RM Length L Ch R = 1 ,8824    ,490.84,474.02,450.69
XS GIS Cut Line= 4
2147792.00675404 726902.468391242147154.83876544726628.966960847
2146583.79208761726565.8510458472146051.81685674726665.033012033
#Sta/Elev= 30
       0  202.94    94.5  200.85  231.22  193.64  246.84  193.96  289.26  191.39
   369.3  190.76  444.04  187.14  482.61  187.92  521.67  186.01  560.89  185.66
  629.47   187.2  678.34  185.25  781.47  176.16  807.92  174.91  896.57  175.11
  905.18  173.69  913.75  175.24  930.88  176.05  976.25  173.36  997.13  174.46
  1050.4  173.61 1088.51  174.35 1117.44  177.46 1192.23  192.77  1253.1  199.48
  1483.1  211.88 1628.81  217.31 1668.04  220.79  1701.2  221.21 1809.05  226.12
#Mann= 5 ,-1,0
       0     .09       0  807.92     .07       0  896.57     .05       0
  913.75     .07       0 1088.51     .09       0
Bank Sta=896.57,913.75
XS Rating Curve= 0 ,0
Exp/Cntr=0.3,0.1