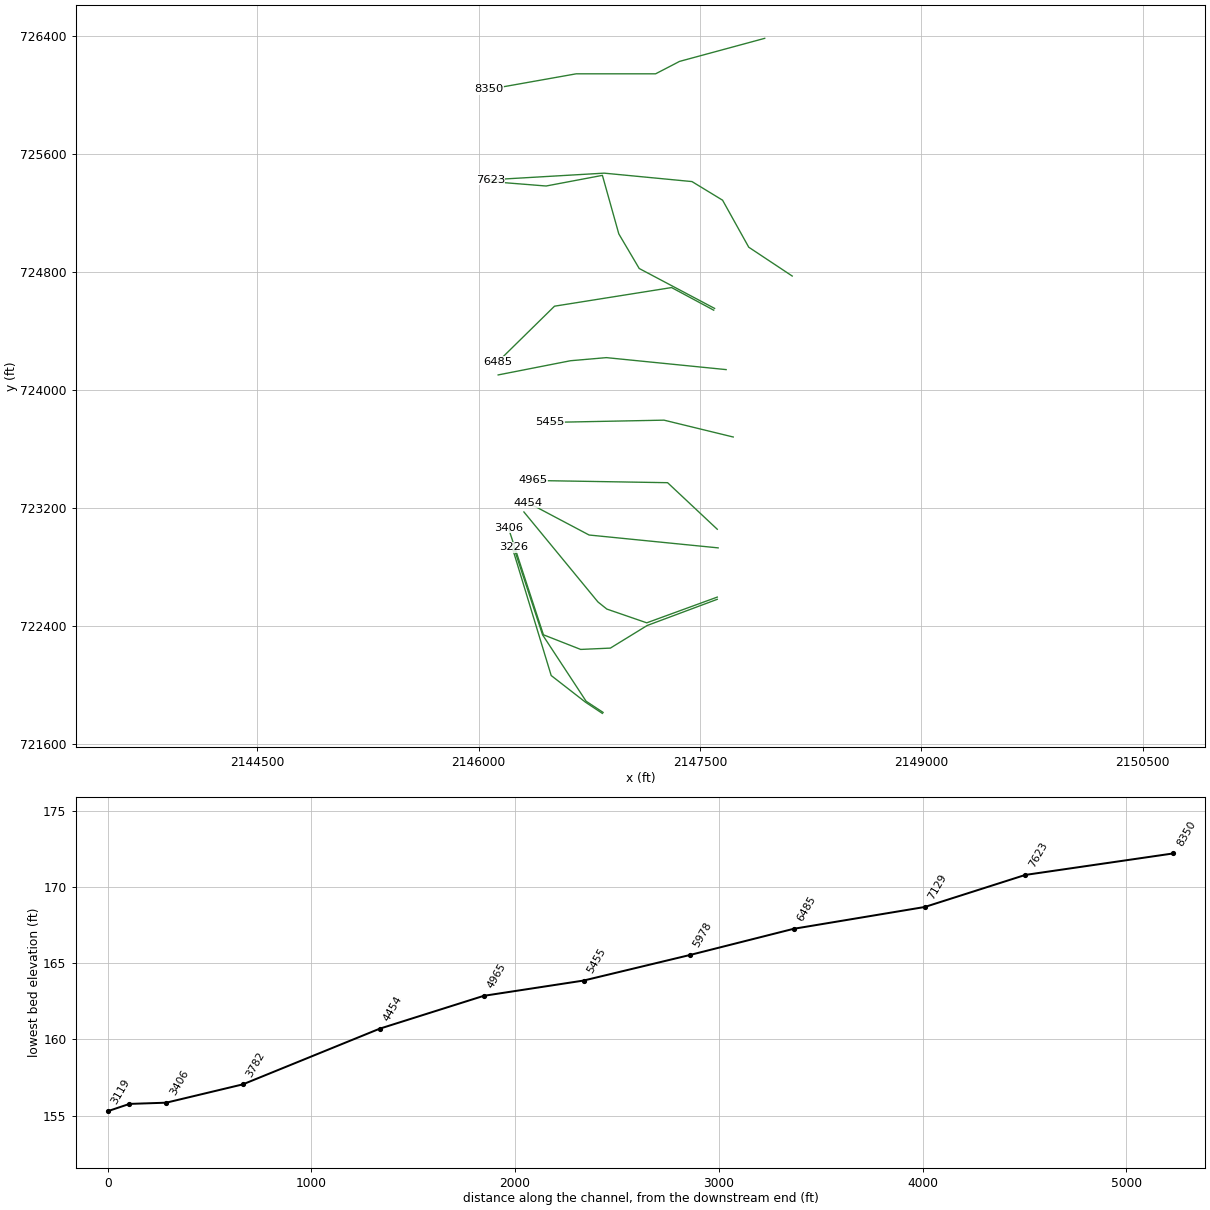
HEC-RAS study R-2829B_Basin15_Strm7_NC540.prj: R-2829B_Basin15_Strm7_I540

--- R-2829B_Basin15_Strm7_NC540.g04 (geometry) --- (continued)

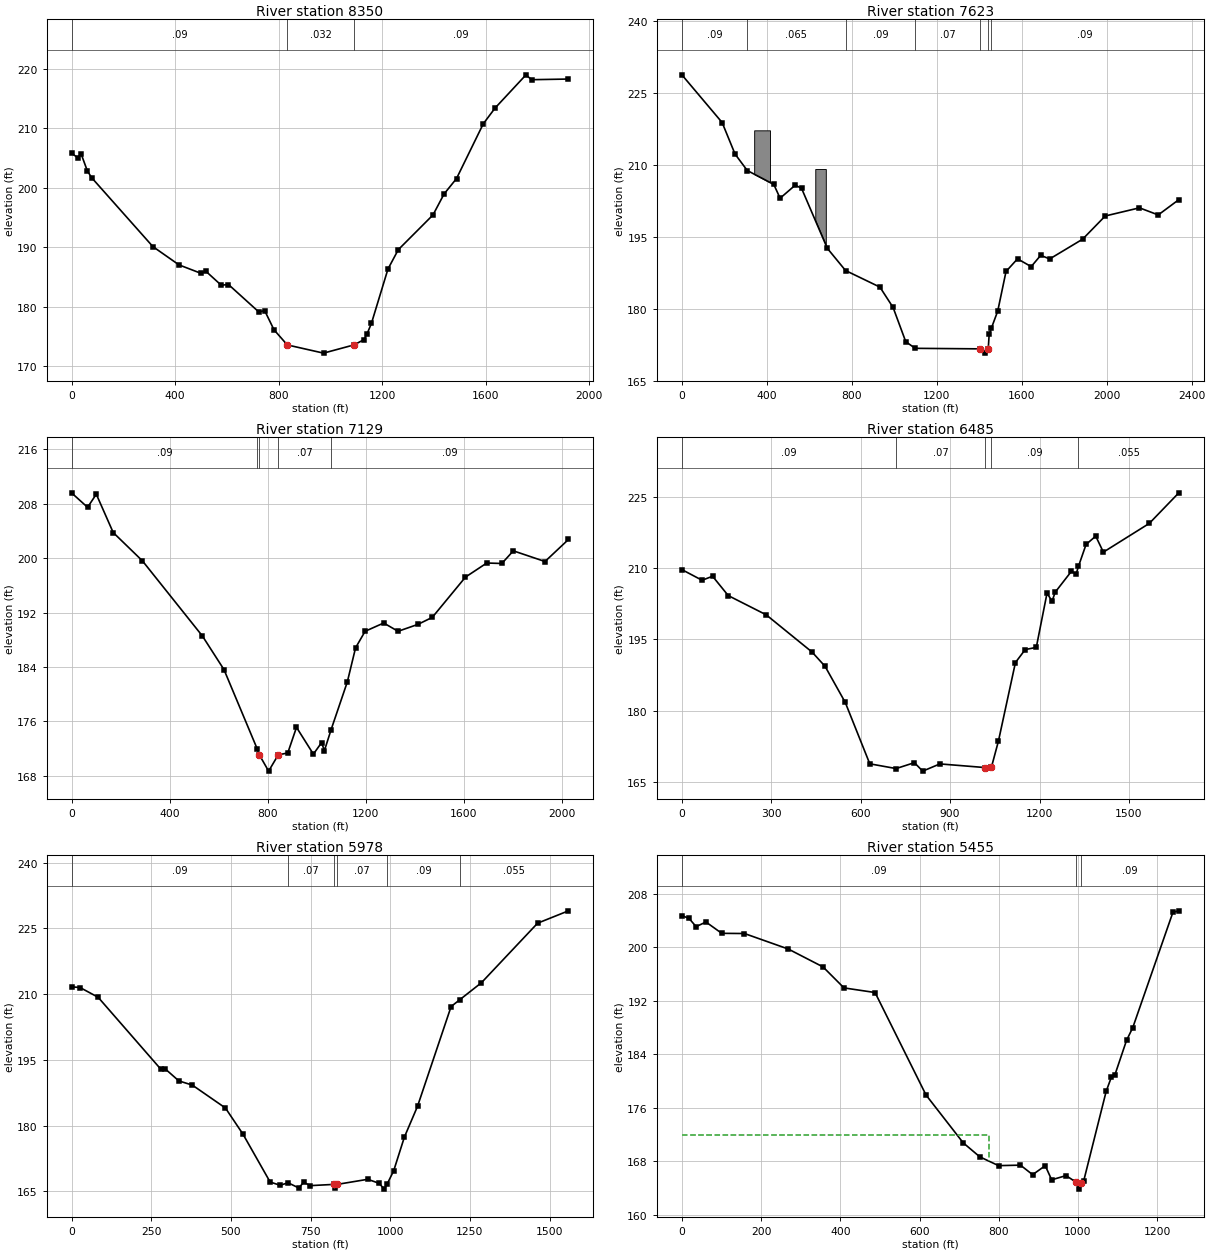
Type RM Length L Ch R = 1 ,8350    ,770.41,727.17,715.64
XS GIS Cut Line= 5
2147939.27700543 726385.520790162147362.21888506726229.234351516
2147199.92165494726145.0800151832146661.93563253726145.080015183
 2146069.8498823726039.887257516
#Sta/Elev= 30
       0  205.85   24.08  205.07   36.64  205.78   61.02  202.88    77.4  201.74
  314.38  190.12  415.35  187.04  500.33  185.62   518.7  185.99   578.5  183.62
  606.41  183.74  723.97  179.11  746.24  179.35  782.32  176.12  833.67  173.57
  973.69  172.19 1091.88  173.58 1129.77  174.46 1141.96  175.44 1158.82   177.2
 1222.71  186.35 1262.59   189.6 1396.68  195.45  1439.5  198.98 1487.51  201.57
  1591.1   210.8 1636.37  213.43 1755.97  219.03 1777.33  218.21 1920.01  218.32
#Mann= 3 ,0,0
       0     .09       0  833.67    .032       0 1091.88     .09       0
Bank Sta=833.67,1091.88
XS Rating Curve= 0 ,0
Exp/Cntr=0.3,0.1

Type RM Length L Ch R = 1 ,7623    ,532.85,493.39,287.9
XS GIS Cut Line= 6
2148125.61870372 724774.56746757  2147831.078852724969.926004112
2147653.75334102 725288.50967288 2147446.3732214725414.741502941
2146851.28272653725471.8459753992146078.86672062725426.763085961
#Sta/Elev= 30
       0  228.78  189.51  218.84  250.25  212.27  307.86  208.84  432.86  205.93
  462.35  203.06  533.52  205.78  563.24  205.14  684.55  192.63  770.35     188
   932.3  184.54  994.29   180.3 1053.85  173.17 1098.33  171.78 1403.43  171.67
 1427.75  170.78 1442.27   171.7 1446.59  174.68 1457.42  176.03 1486.88  179.54
    1526   187.8 1580.02  190.43 1644.41  188.81 1689.17  191.16 1731.61  190.41
 1886.65  194.53 1992.97  199.36 2154.23  201.06 2242.49  199.58 2339.36  202.76
#Mann= 7 ,-1,0
       0     .09       0  307.86    .065       0  770.35     .09       0
 1098.33     .07       0 1403.43     .05       0 1442.27     .07       0
 1457.42     .09       0
#Block Obstruct= 2 ,-1
  340.33   414.7 217.213  627.96  677.56 209.148
Bank Sta=1403.43,1442.27
XS Rating Curve= 0 ,0
Exp/Cntr=0.3,0.1

Type RM Length L Ch R = 1 ,7129    ,389.65,643.98,688.62
XS GIS Cut Line= 6
2147599.65426427724555.1657649872147088.71810573724825.661148489
2146950.46469271725060.0911319852146839.26049244725456.818345606
2146457.56090868725384.6862432962146081.87211639725414.741502941
#Sta/Elev= 30
       0   209.6   65.56  207.47  101.11   209.4  170.13  203.76  289.27   199.6
  534.23  188.54  622.12  183.61  757.93  171.93  765.97   171.1  804.25  168.68
  843.31  171.06  882.51  171.36  917.98  175.12   986.9  171.18 1020.14  172.86
 1032.05  171.71 1059.24  174.78 1125.31  181.79 1159.05  186.81 1197.95  189.24
 1273.89  190.46  1332.5  189.24 1413.72  190.26 1472.13  191.29 1607.54  197.21
 1694.39  199.28 1755.86  199.21 1802.74  201.07 1931.94   199.5 2027.64  202.74
#Mann= 5 ,-1,0
       0     .09       0  757.93     .07       0  765.97     .05       0
  843.31     .07       0 1059.24     .09       0
Bank Sta=765.97,843.31
XS Rating Curve= 0 ,0
Exp/Cntr=0.3,0.1

Type RM Length L Ch R = 1 ,6485    ,416.32,507.28,396.75
XS GIS Cut Line= 4
2147593.64347279724543.1435309052147308.11980832724696.424573779
2146514.66538113724570.1927437192146129.53068727724191.936082959
#Sta/Elev= 30
       0  209.69   67.73  207.45     103  208.29  155.56  204.22  282.91  200.17
   437.1  192.31  480.53  189.31  548.23  181.71  630.47  168.79  718.78  167.79
  780.15  169.03  808.07  167.25  865.77  168.77 1015.56  168.01 1038.39  168.02
 1062.02  173.55 1119.17  190.12 1151.94  192.85 1189.14  193.31 1225.12  204.72
 1242.12  203.04 1252.64  204.94 1307.23  209.35  1322.9  208.76 1330.52  210.35
 1356.14  214.99 1388.56  216.74 1414.22  213.37 1568.29  219.42 1667.32  225.86
#Mann= 5 ,-1,0
       0     .09       0  718.78     .07       0 1015.56     .05       0
 1038.39     .09       0 1330.52    .055       0
Bank Sta=1015.56,1038.39
XS Rating Curve= 0 ,0
Exp/Cntr=0.3,0.1

Type RM Length L Ch R = 1 ,5978    ,434.95,523.64,425.46
XS GIS Cut Line= 4
2147677.79780912724140.4048746822146866.31035632724221.553815305
2146622.86418563724200.5153939722146132.96579731724104.338823557
#Sta/Elev= 30
       0  211.67   26.79  211.51   83.49  209.29  280.25  192.88  294.27  192.94
  336.75  190.22  379.12  189.26  482.91  184.04  538.04  178.07  623.17  167.16
  654.48  166.42  679.47  166.99  713.27   165.8  728.01   167.1  749.69  166.34
  823.85  166.62  828.13  165.74   831.8   166.6  929.44  167.78  965.19  166.87
  980.96  165.54  990.99   166.8  1010.8  169.72 1044.32  177.39 1085.63  184.43
 1190.94  207.17 1217.84  208.71  1286.2  212.61 1462.34  226.18 1559.14     229
#Mann= 6 ,-1,0
       0     .09       0  679.47     .07       0  823.85     .05       0
   831.8     .07       0  990.99     .09       0 1217.84    .055       0
Bank Sta=823.85,831.8
XS Rating Curve= 0 ,0
Exp/Cntr=0.3,0.1

Type RM Length L Ch R = 1 ,5455    ,423.17,489.95,412.34
XS GIS Cut Line= 3
2147725.88609433723683.567792892 2147257.0261274723797.777388871
 2146485.2325561723782.669675946
#Sta/Elev= 30
       0   204.7   17.88   204.3   35.92  203.06   60.82  203.75  100.65  202.06
  157.98  202.03  268.84  199.71  356.44  197.04  409.25  193.91  487.68  193.22
  616.42  177.91  710.13  170.78  752.15  168.68  799.34  167.37  854.77  167.44
  885.48  166.02  917.32  167.36  933.54  165.25  969.84  165.88  996.08  164.86
 1002.31  163.86  1008.6  164.84 1014.06  165.01 1071.31   178.5 1084.21  180.57
 1093.38  180.96 1122.46  186.06 1138.29  187.98 1239.62   205.2 1254.51  205.42
#Mann= 3 ,0,0
       0     .09       0  996.08     .05       0  1008.6     .09       0
#XS Ineff= 2 , 0
       0     775     172               0
Permanent Ineff=
       F       F
Bank Sta=996.08,1008.6
XS Rating Curve= 0 ,0
Exp/Cntr=0.3,0.1

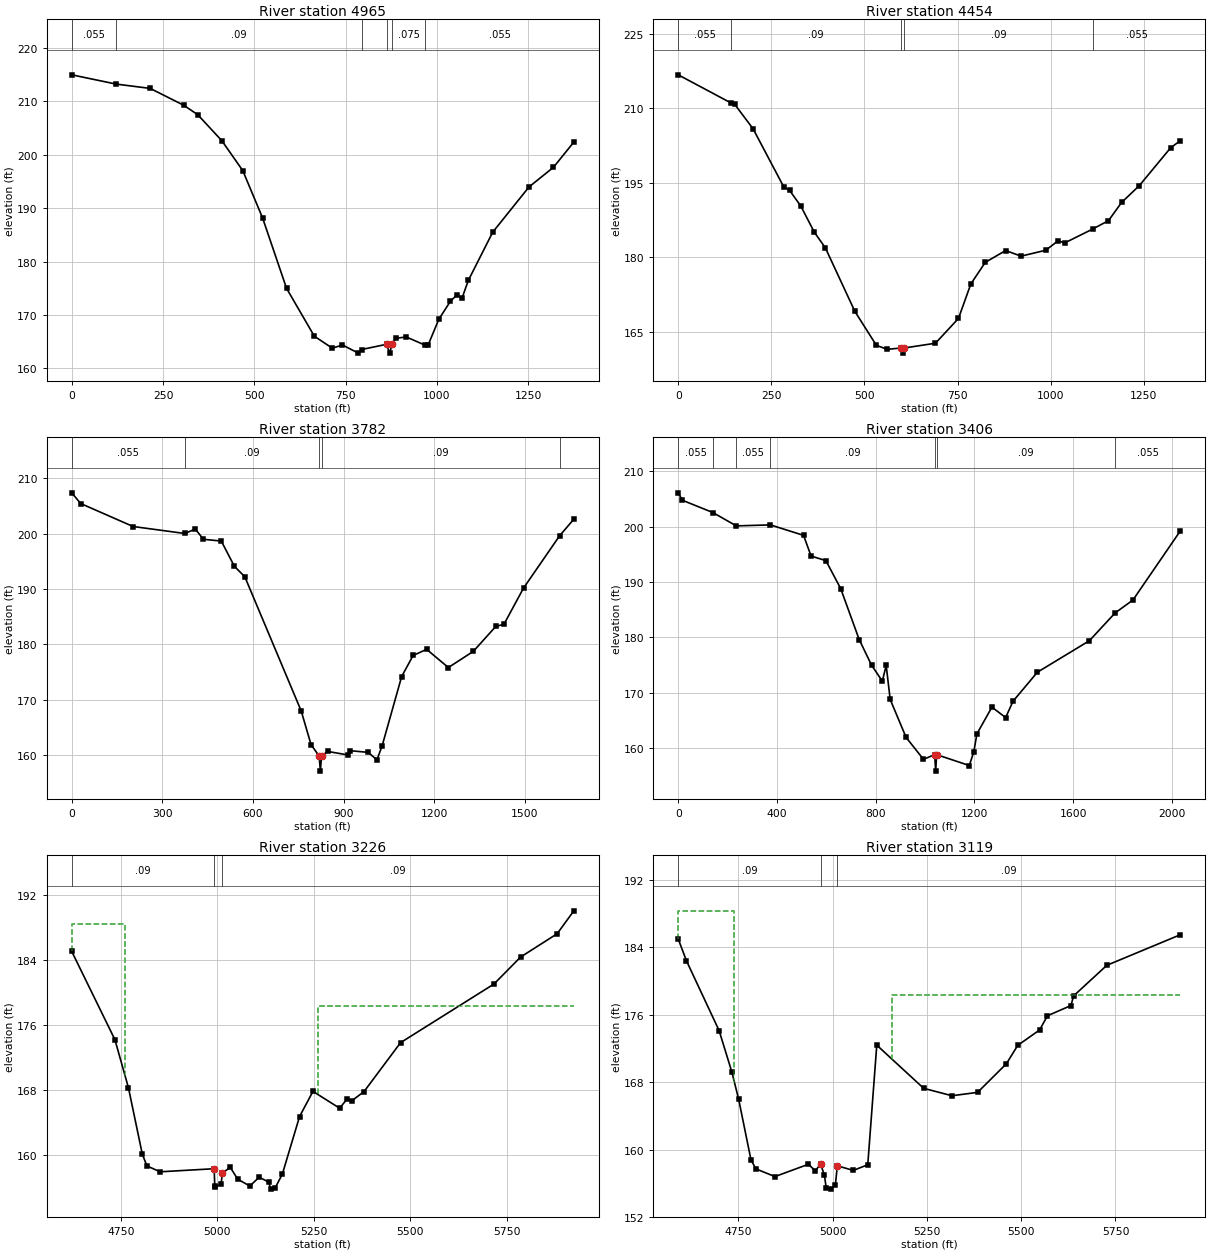
Type RM Length L Ch R = 1 ,4965    ,400.65,510.18,395.6
XS GIS Cut Line= 3
2147617.68728983723058.422038376 2147281.0705955723374.000311375
 2146367.3957808723389.027941167
#Sta/Elev= 30
       0  214.92  121.43  213.19  214.75  212.38  306.31  209.24  345.12  207.46
  411.23  202.58  468.41     197  522.82  188.12  588.21  174.99  664.44  166.02
  713.52  163.79   741.5  164.38  785.02  162.86  793.63  163.53  862.16  164.51
  870.44  162.86   877.5  164.51  887.83  165.64   916.4  165.88   968.7  164.32
  976.03  164.36 1005.35  169.19 1037.26  172.57 1054.67  173.73 1069.03  173.15
 1086.09  176.45 1153.06  185.49 1252.48  193.95 1319.32  197.62 1375.21  202.34
#Mann= 6 ,-1,0
       0    .055       0  121.43     .09       0  793.63    .075       0
  862.16     .05       0   877.5    .075       0   968.7    .055       0
Bank Sta=862.16,877.5
XS Rating Curve= 0 ,0
Exp/Cntr=0.3,0.1

Type RM Length L Ch R = 1 ,4454    ,521.21,672.36,407.43
XS GIS Cut Line= 3
2147623.69873244722932.1902082562146749.09536457 723019.34994036
2146334.33512539723238.752294064
#Sta/Elev= 30
       0   216.7  142.23  211.02  151.35  210.79  200.93  205.85  283.44  194.14
  299.24  193.43  329.21  190.29  365.23  185.06  394.98   181.9  474.27  169.11
  532.08  162.27  561.44  161.47  599.12  161.75  603.36  160.71  607.37  161.75
   690.6   162.7  752.49  167.69  785.69  174.63  824.56  178.98  879.17  181.35
  920.58  180.22  986.91  181.41 1019.98  183.31  1037.7  182.88  1113.3  185.69
 1155.28  187.36 1190.56  191.03 1237.87  194.39 1322.18  202.02 1348.15  203.45
#Mann= 5 ,-1,0
       0    .055       0  142.23     .09       0  599.12     .05       0
  607.37     .09       0  1113.3    .055       0
Bank Sta=599.12,607.37
XS Rating Curve= 0 ,0
Exp/Cntr=0.3,0.1

Type RM Length L Ch R = 1 ,3782    ,299.14,375.9,397.77
XS GIS Cut Line= 5
2147617.68728983722598.5789096952147139.81178671722424.259445488
2146869.31575209722517.429969072 2146809.2052328 722565.51825434
2146307.28526151723175.636379004
#Sta/Elev= 30
       0  207.38   29.32  205.45  202.96  201.29  373.74  200.03  409.02  200.82
  435.68  198.98  494.84  198.66  538.42  194.08  572.82   192.2  759.57  167.91
  791.87  161.86   818.6   159.8  822.91  157.06  826.57   159.8   847.2  160.62
  913.31  159.99  920.95  160.76  981.14  160.45 1010.03  159.09  1027.5  161.68
  1091.8  174.15 1129.71  177.97 1174.61  179.08 1246.45  175.79  1329.2  178.72
 1403.53  183.23 1430.47  183.61 1495.18  190.15 1615.26  199.66 1661.79  202.61
#Mann= 5 ,-1,0
       0    .055       0  373.74     .09       0   818.6     .05       0
  826.57     .09       0 1615.26    .055       0
Bank Sta=818.6,826.57
XS Rating Curve= 0 ,0
Exp/Cntr=0.3,0.1

Type RM Length L Ch R = 1 ,3406    ,264.58,180.61,105.39
XS GIS Cut Line= 6
2147617.68728983722583.5512799022147142.81718248722406.226419926
2146893.35956913722252.9453770522146691.99089217 722243.92853874
2146439.52788311722343.1105049252146202.09250385723067.438225567
#Sta/Elev= 30
       0  206.11   16.61  204.77   140.4  202.55  235.42  200.14  373.58  200.32
  507.86  198.43  538.43  194.69  598.36  193.87  658.38  188.82  733.34  179.62
  783.24  175.01  827.05  172.11  842.78  174.94  858.98   168.8  923.46  161.95
  993.82  157.99 1039.11  158.84  1043.4  155.86 1047.07  158.84 1179.63  156.87
 1198.14   159.4 1210.41  162.59 1271.29  167.41 1326.94  165.53  1356.6  168.47
 1455.54  173.72 1666.33  179.41 1770.23  184.41 1842.83  186.76 2034.75  199.23
#Mann= 7 ,-1,0
       0    .055       0   140.4     .09       0  235.42    .055       0
  373.58     .09       0 1039.11     .05       0 1047.07     .09       0
 1770.23    .055       0
#XS Ineff= 2 , 0
                         1271.85          167.12
Permanent Ineff=
       F       F
Bank Sta=1039.11,1047.07
XS Rating Curve= 0 ,0
Exp/Cntr=0.3,0.1

Type RM Length L Ch R = 1 ,3226    ,52.18,106.95,84.48
XS GIS Cut Line= 4
    2146843.9166     721817.1018    2146728.9405     721892.7372
    2146433.8252     722342.6326    2146237.5417     722937.3186
#Sta/Elev= 30
 4622.29     185 4734.16  174.16 4769.27  168.24 4805.15  160.09 4817.11  158.64
 4851.14  157.91 4991.56  158.29 4993.06  156.21 4994.88  156.07 5009.35  156.37
  5012.9  157.74 5033.14  158.47 5052.64     157 5084.05  156.16 5108.22  157.25
 5133.47  156.63 5137.72  155.78 5149.71  155.93 5168.41  157.64    5213  164.71
  5247.7   167.8  5316.9  165.73  5336.6  166.89 5348.49  166.65 5380.09  167.77
 5474.87  173.79 5717.11     181 5786.23  184.32 5880.85  187.18 5924.21     190
#Mann= 3 ,0,0
 4622.29     .09       0 4991.56     .05       0  5012.9     .09       0
#XS Ineff= 2 , 0
          4760.9  188.35  5259.5          178.35
Permanent Ineff=
       F       F
Bank Sta=4991.56,5012.9
XS Rating Curve= 0 ,0
Exp/Cntr=0.5,0.3

Type RM Length L Ch R = 1 ,3119    ,153.86,218.92,74.22
BEGIN DESCRIPTION:
Upstream Y29RPD
END DESCRIPTION:
XS GIS Cut Line= 4
    2146838.6554     721810.5489    2146724.6658     721886.3471
    2146492.2038     722067.0229    2146230.4001     722927.4661
#Sta/Elev= 30
 4591.14     185 4612.98  182.41 4699.51  174.12 4733.36  169.19 4751.19  165.99
 4783.78  158.81 4796.68  157.71 4847.37  156.79 4936.03  158.25  4954.8  157.47
 4968.27  158.29 4978.47  156.97 4983.39  155.43 4995.65   155.3  5007.5  155.74
 5012.76  158.07 5055.23  157.52 5093.48   158.2 5117.34   172.4 5241.68  167.27
 5316.69  166.39 5384.56  166.79 5460.87  170.19 5490.92  172.37 5548.86   174.2
 5569.76  175.89 5631.91   177.1 5639.07  178.25 5727.07  181.88 5921.84  185.51
#Mann= 3 ,0,0
 4591.14     .09       0 4968.27     .05       0 5012.76     .09       0
#XS Ineff= 2 , 0
          4740.2  188.35  5158.8          178.35
Permanent Ineff=
       F       F
Bank Sta=4968.27,5012.76
XS Rating Curve= 0 ,0
Exp/Cntr=0.5,0.3