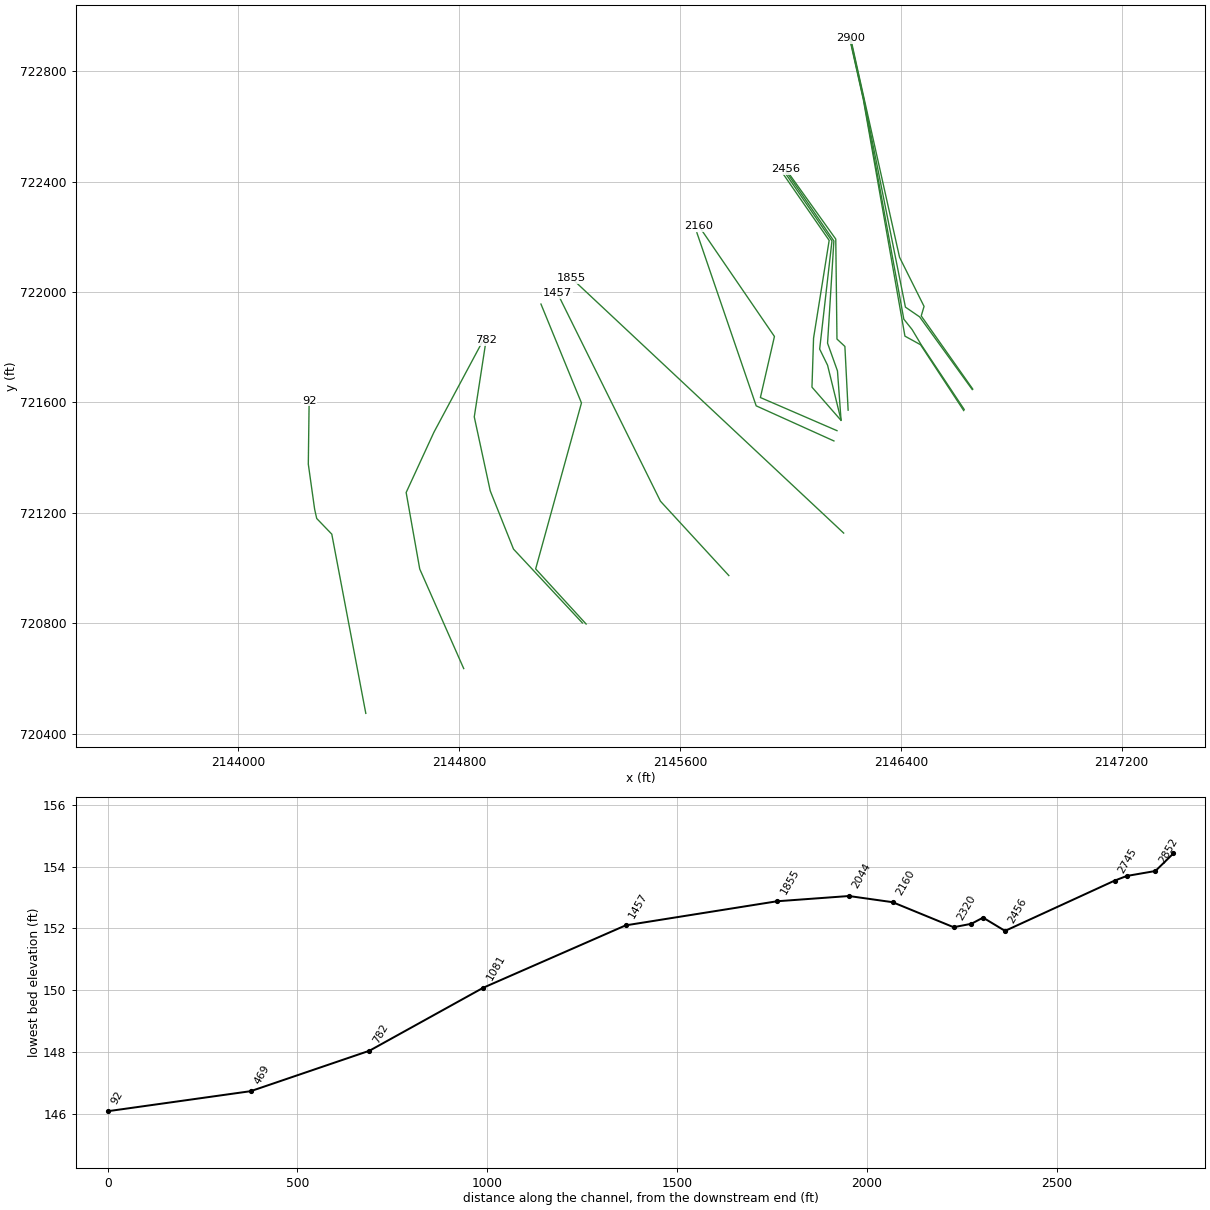
HEC-RAS study R-2829B_Basin15_Strm7_NC540.prj: R-2829B_Basin15_Strm7_I540

--- R-2829B_Basin15_Strm7_NC540.g04 (geometry) --- (continued)

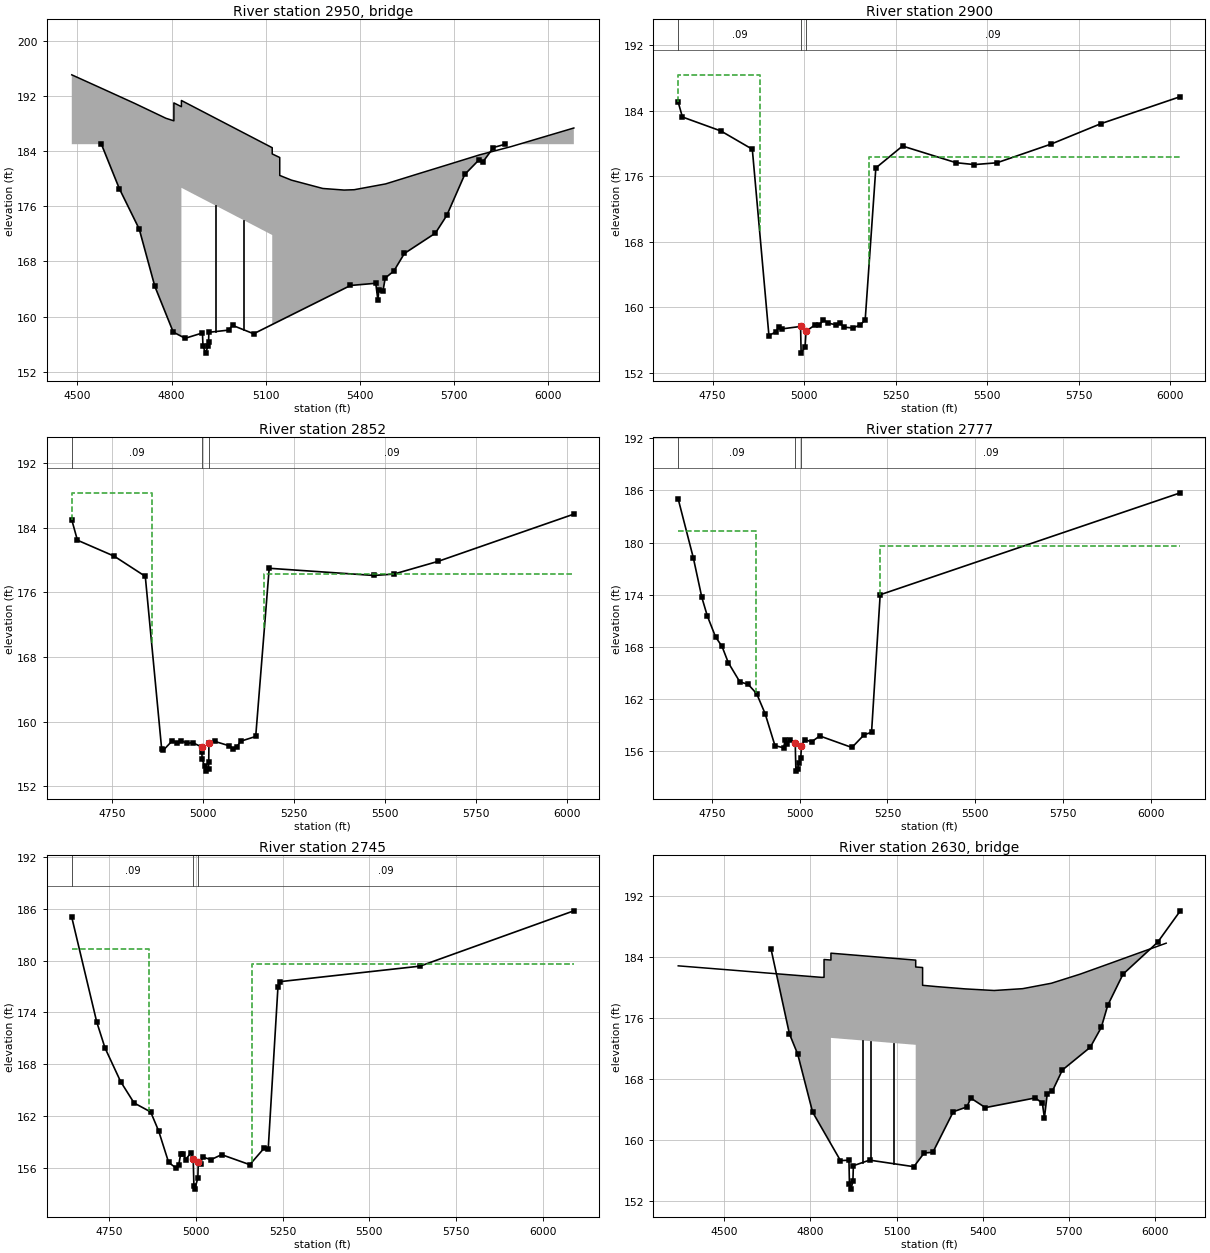
Type RM Length L Ch R = 3 ,2950    ,,,
BEGIN DESCRIPTION:
Y29RPD
END DESCRIPTION:
Bridge Culvert--1,0,-1,-1, 0
Deck Dist Width WeirC Skew NumUp NumDn MinLoCord MaxHiCord MaxSubmerge Is_Ogee
144.5,34.4,2.6,0, 23, 23, , , 0.98, 0, 2,2,,
    4482    4582    4682    4782  4807.4  4807.4  4831.4  4831.4  5120.8  5120.8
  5144.8  5144.8    5182    5282 5349.81    5382    5482    5582    5682    5782
    5882    5982    6082
  195.06     193  190.93  188.76  188.39  190.99  190.44  191.34  184.49  183.59
  183.07  180.47  179.79  178.58  178.35   178.4  179.24  180.65  182.05  183.46
  184.65     186  187.35
                                                          178.68  171.83
                                                                                
                        
    4532    4632    4732    4832  4857.4  4857.4  4881.4  4881.4  5170.8  5170.8
  5194.8  5194.8    5232    5332 5399.81    5432    5532    5632    5732    5832
    5932    6032    6132
  195.06     193  190.93  188.76  188.39  190.99  190.44  191.34  184.49  183.59
  183.07  180.47  179.79  178.58  178.35   178.4  179.24  180.65  182.05  183.46
  184.65     186  187.35
                                                          178.68  171.83
                                                                                
                        
Pier Skew, UpSta & Num, DnSta & Num=  ,4938.9, 2 ,4988.9, 2 , 0 , 0 , 0 ,,
     3.5     3.5
     150  179.65
     3.5     3.5
     150  179.65
Pier Skew, UpSta & Num, DnSta & Num=  ,5030.5, 2 ,5080.5, 2 , 0 , 0 , 0 ,,
     3.5     3.5
     150  179.65
     3.5     3.5
     150  179.65
Abutment Skew #Up #Dn= , 5 , 5
  4831.4 4834.19 4834.19 4835.79 4910.79
  178.68  178.68  175.68  175.68  125.68
  4881.4 4884.19 4884.19 4885.79 4960.79
  178.68  178.68  175.68  175.68  125.68
Abutment Skew #Up #Dn= , 5 , 5
 5041.41 5116.41 5118.01 5118.01  5120.8
  118.83  168.83  168.83  171.84  171.83
 5091.41 5166.41 5168.01 5168.01  5170.8
  118.83  168.83  168.83  171.84  171.83
BR Coef=-1 , 1 , 0 ,, 0 ,,,0.8,0,1.2,0,
WSPro=,,,, 1 ,,,, 0 ,,,, 0 ,,,,-1 ,-1 ,-1 , 0 , 0 , 0 , 0 , 0
BR U #Sta/Elev= 30
 4576.42     185 4633.49  178.56 4696.98  172.69 4746.64  164.39 4805.41  157.75
 4843.34  156.85  4898.5  157.63 4900.17  155.69 4908.83   154.7 4916.52   155.8
 4918.05   156.3 4918.81  157.72 4982.14  158.04 4994.21  158.73 5061.69  157.51
 5370.21  164.51 5450.69  164.83 5457.63  162.36 5460.67  163.88 5473.52  163.66
 5480.95  165.59 5508.39   166.6 5541.95  169.15 5640.82   172.1 5677.09  174.67
  5734.5  180.62 5778.93  182.69 5791.89  182.41 5825.88  184.52 5863.38     185
BR U #Mann= 3
 4576.42     .09  4898.5     .05 4918.81     .09
BR U Banks=4898.5,4918.81
BR D #Sta/Elev= 30
 4626.42     185 4683.49  178.56 4746.98  172.69 4796.64  164.39 4855.41  157.75
 4893.34  156.85 4930.13  157.88 4949.48  157.42 4951.63  155.82 4958.83  154.56
 4964.94   155.4 4967.42  157.77 5032.14  158.04 5044.21  158.73 5111.69  157.51
 5420.21  164.51 5500.69  164.83 5507.63  162.36 5510.67  163.88 5523.52  163.66
 5530.95  165.59 5558.39   166.6 5591.95  169.15 5690.82   172.1 5727.09  174.67
  5784.5  180.62 5828.93  182.69 5841.89  182.41 5875.88  184.52 5913.38     185
BR D #Mann= 3
 4626.42     .09 4949.48     .05 4967.42     .09
BR D Banks=4949.48,4967.42
BC Design=,, 0 ,, 0 ,,,,,,
BC Use User HTab Curves=0
BC User HTab FreeFlow(D)= 0

Type RM Length L Ch R = 1 ,2900    ,6.07,47.59,29.49
BEGIN DESCRIPTION:
Downstream Y29RPD
END DESCRIPTION:
XS GIS Cut Line= 5
    2146660.4483     721648.3271     2146473.749     721913.2838
    2146483.9778     721947.8159    2146395.2282     722125.7746
     2146218.144     722918.7873
#Sta/Elev= 30
 4656.08     185 4667.45  183.21 4772.49  181.51 4858.44  179.28 4903.86  156.56
 4923.22  157.04  4930.4  157.58 4940.17  157.39 4990.31  157.68 4991.79  154.43
  5002.6   155.2 5005.19  157.08 5030.47   157.9 5041.65  157.86 5052.82   158.5
 5064.79  158.09 5086.35  157.89 5097.53  158.07  5108.7  157.59 5132.76   157.5
  5153.4  157.86 5166.82   158.5 5195.87     177 5268.72  179.67 5415.02  177.64
 5465.05  177.41 5526.65  177.63 5674.09   179.9 5810.26  182.39 6027.63  185.69
#Mann= 3 ,0,0
 4656.08     .09       0 4990.31     .05       0 5005.19     .09       0
#XS Ineff= 2 , 0
       0 4878.95  188.35 5177.32       0  178.35
Permanent Ineff=
       F       F
Bank Sta=4990.31,5005.19
XS Rating Curve= 0 ,0
Exp/Cntr=0.5,0.3

Type RM Length L Ch R = 1 ,2852    ,47.84,75.14,13.17
XS GIS Cut Line= 5
    2146658.6097     721646.5736    2146467.8954     721909.9545
    2146416.4703     721945.1774    2146266.4026     722695.7562
    2146216.7734     722918.3148
#Sta/Elev= 30
 4638.42     185 4653.93  182.48 4755.13   180.5 4840.63     178 4885.74  156.57
 4890.26  156.45 4914.96  157.63  4927.3  157.39 4939.65  157.63 4955.68   157.3
 4970.64  157.39 4995.68  156.86 4996.34  156.28  4996.9  155.31 5003.52  154.55
 5006.51  153.86  5014.5  154.18 5015.15  154.99 5015.66  157.38 5031.42  157.55
 5072.23  156.99 5082.42  156.64 5092.62  156.87 5102.82  157.56 5144.35  158.16
 5181.45     179 5469.19  178.11 5524.33  178.28 5646.22  179.86 6019.39  185.71
#Mann= 3 ,0,0
 4638.42     .09       0 4995.68     .05       0 5015.66     .09       0
#XS Ineff= 2 , 0
          4857.9  188.35  5168.2          178.35
Permanent Ineff=
       F       F
Bank Sta=4995.68,5015.66
XS Rating Curve= 0 ,0
Exp/Cntr=0.5,0.3

Type RM Length L Ch R = 1 ,2777    ,44.24,32.06,6.42
XS GIS Cut Line= 6
    2146629.2785     721574.6272    2146473.3007     721809.4642
    2146440.7223      721863.973     2146410.718     721901.5015
    2146265.2546     722695.9221    2146215.6968     722917.9437
#Sta/Elev= 30
 4654.58     185 4697.68  178.22 4721.69   173.7 4737.35  171.56 4760.93  169.13
 4779.01  168.07 4797.08  166.18 4829.74  163.98 4853.76  163.68 4877.77  162.61
 4901.78  160.32 4929.81  156.63  4954.4  156.39 4958.48  157.23 4962.87  156.79
 4972.96  157.33  4987.5  156.89 4989.33   153.7  4994.3  153.91 4997.39  154.65
 5003.28  155.24  5005.2  156.61 5014.66  157.33 5034.04  157.07 5057.24  157.75
 5148.77  156.42 5183.42  157.88 5204.63  158.17 5229.17     174 6083.17  185.73
#Mann= 3 ,0,0
 4654.58     .09       0  4987.5     .05       0  5005.2     .09       0
#XS Ineff= 2 , 0
       0 4876.28  181.28  5229.4       0  179.56
Permanent Ineff=
       F       F
Bank Sta=4987.5,5005.2
XS Rating Curve= 0 ,0
Exp/Cntr=0.5,0.3

Type RM Length L Ch R = 1 ,2745    ,228.82,288.83,267.73
BEGIN DESCRIPTION:
Upstream NC 540
END DESCRIPTION:
XS GIS Cut Line= 5
    2146627.5999     721570.5221    2146471.2262     721809.0296
    2146414.6987     721840.0852    2146264.1795     722696.2867
    2146214.6696     722917.5896
#Sta/Elev= 30
 4643.01     185 4714.76  172.91 4738.68  169.89 4783.74  165.99  4822.4  163.52
 4870.23  162.48 4893.19  160.28 4921.95  156.64 4943.75  155.98 4950.86  156.29
 4956.38  157.57 4964.46  157.64 4970.91  156.97 4986.33  157.76 4992.71  157.05
 4994.71  153.89  4997.1  153.55 5006.05  154.83 5007.37  156.67 5014.32  156.48
 5019.68  157.27 5043.95  156.96 5074.53  157.54 5155.65  156.38 5196.27  158.26
  5208.6  158.14 5236.67  176.88 5243.51  177.56 5645.87  179.35 6088.81  185.75
#Mann= 3 ,0,0
 4643.01     .09       0 4992.71     .05       0 5007.37     .09       0
#XS Ineff= 2 , 0
       0 4865.45  181.28    5163       0  179.56
Permanent Ineff=
       F       F
Bank Sta=4992.71,5007.37
XS Rating Curve= 0 ,0
Exp/Cntr=0.5,0.3

Type RM Length L Ch R = 3 ,2630    ,,,
BEGIN DESCRIPTION:
NC 540
END DESCRIPTION:
Bridge Culvert--1,0,-1,-1, 0
Deck Dist Width WeirC Skew NumUp NumDn MinLoCord MaxHiCord MaxSubmerge Is_Ogee
19,171.9,2.6,0, 23, 23, , , 0.98, 0, 2,2,,
  4339.5  4439.5  4539.5  4639.5  4739.5  4839.5  4847.5  4847.5  4871.5  4871.5
  5166.9  5166.9  5190.9  5190.9  5239.5  5339.5 5440.05  5539.5  5639.5  5739.5
  5839.5  5939.5  6039.5
  182.79  182.49  182.19  181.88  181.58  181.28  181.29  183.62  183.55  184.45
  183.54  182.64  182.57  180.24  180.07  179.77  179.56   179.8  180.51   181.7
  183.05  184.41  185.76
                                                                          173.35
  172.44
                        
  4339.5  4439.5  4539.5  4639.5  4739.5  4839.5  4847.5  4847.5  4871.5  4871.5
  5166.9  5166.9  5190.9  5190.9  5239.5  5339.5 5440.05  5539.5  5639.5  5739.5
  5839.5  5939.5  6039.5
  182.79  182.49  182.19  181.88  181.58  181.28  181.29  183.62  183.55  184.45
  183.54  182.64  182.57  180.24  180.07  179.77  179.56   179.8  180.51   181.7
  183.05  184.41  185.76
                                                                          173.35
  172.44
                        
Pier Skew, UpSta & Num, DnSta & Num=  ,4979.8, 2 ,4979.8, 2 , 0 , 0 , 0 ,,
     3.5     3.5
     150  173.35
     3.5     3.5
     150  173.35
Pier Skew, UpSta & Num, DnSta & Num=  ,5009.4, 2 ,5009.4, 2 , 0 , 0 , 0 ,,
     3.5     3.5
     150  173.35
     3.5     3.5
     150  173.35
Pier Skew, UpSta & Num, DnSta & Num=  ,5088.2, 2 ,5088.2, 2 , 0 , 0 , 0 ,,
     3.5     3.5
     150  173.35
     3.5     3.5
     150  173.35
Abutment Skew #Up #Dn= , 5 , 5
  4871.5 4874.33 4874.33 4876.03 4951.03
  173.35  173.35  170.35  170.35  120.35
  4871.5 4874.33 4874.33 4876.03 4951.03
  173.35  173.35  170.35  170.35  120.35
Abutment Skew #Up #Dn= , 5 , 5
 5087.37 5162.37 5164.07 5164.07  5166.9
  119.44  169.44  169.44  172.44  172.44
 5087.37 5162.37 5164.07 5164.07  5166.9
  119.44  169.44  169.44  172.44  172.44
BR Coef=-1 , 1 , 0 ,, 0 ,,,0.8,0,1.2,0,
WSPro=,,,, 1 ,,,, 0 ,,,, 0 ,,,,-1 ,-1 ,-1 , 0 , 0 , 0 , 0 , 0
BR U #Sta/Elev= 30
 4662.77     185 4726.86  173.88 4755.81  171.21 4807.68  163.62 4904.72  157.27
 4934.26  157.32 4936.05  154.18 4941.37  153.53 4948.02  154.54 4949.69   156.6
 5006.13  157.33  5160.5  156.47 5196.27  158.26 5226.73  158.36 5297.81  163.67
  5345.3   164.3 5358.74  165.46 5409.51  164.21 5583.35  165.48 5608.13   164.8
 5615.32  162.85 5625.28  166.06 5643.06  166.38 5677.95  169.14 5775.07  172.12
 5813.47  174.72    5836  177.62 5889.21   181.7 6009.98  185.89 6088.81     190
BR U #Mann= 3
 4662.77     .09 4934.26     .05 4949.69     .09
BR U Banks=4934.26,4949.69
BR D #Sta/Elev= 198
 4735.44     185 4744.01  184.22 4745.99  184.03 4754.02  183.37 4756.54  183.36
 4764.04  183.04 4767.09  182.79 4774.05  182.33 4777.64  182.11 4784.06  181.67
 4788.19  181.43 4794.08  181.21 4806.12   180.5 4808.13  180.38 4809.88   179.9
 4824.12  175.96 4830.39  174.63 4834.13  173.76 4840.94  171.63 4844.15  170.64
 4849.81   168.7 4856.44  166.38 4862.95  161.75 4864.18   160.6 4868.36  158.65
  4870.9  157.24 4873.23  154.88 4873.43  154.81 4876.13  154.81  4881.6  154.83
 4884.13  154.42  4884.3  154.37 4884.81  154.36 4889.33  154.32  4890.5  154.98
 4890.83   155.2 4899.96  155.44  4909.3   155.8 4911.58  155.75 4919.32   155.8
 4922.47  155.38 4922.71  155.39 4929.34  156.06 4933.03  156.09 4939.37  156.28
 4943.75   156.2 4949.39  156.02 4954.48  156.48 4959.41  156.84  4965.2   156.9
 4969.43  156.74 4975.92  156.46 4979.45   156.5 4986.68  156.58 4989.48   156.6
 4991.94   156.6 5005.25  156.72 5009.91  156.81  5010.7  156.81  5015.4  156.53
 5016.34  156.49 5018.59  156.32  5018.6  156.32 5019.24  156.16 5019.97  156.07
 5020.44  156.01  5020.8  155.99 5025.84  155.66 5027.35  154.31 5027.83  153.62
 5029.43  153.16  5031.5  152.57 5042.98  153.25 5045.69  153.59 5046.27  153.86
 5047.27  155.47 5049.12  155.87 5056.52  155.47 5057.78  155.49 5058.18  155.54
 5077.69  156.14 5078.75  156.11 5079.85  155.84 5080.86  155.65 5083.03   155.6
 5084.53  155.52 5086.02  156.04 5086.81  156.34 5096.58  157.06 5104.73  157.79
 5105.74   157.8 5107.06  157.93 5115.83  158.72 5118.73  158.91 5125.92  159.22
  5130.4  159.47 5136.01  159.86 5142.07  160.37 5146.11  160.63 5153.74  161.54
  5156.2  161.78  5165.4  162.69 5166.29  162.78 5171.96  162.97 5176.38  163.13
 5177.07  163.23 5180.78  163.85 5186.82  164.47  5190.9   164.6 5196.82   165.1
 5201.02  165.61 5206.82  166.06 5211.15  166.57 5216.82  167.13 5221.27  167.69
 5226.82  168.91 5231.39  169.14 5236.83  169.23 5241.52  169.51 5246.83  169.73
 5251.64  170.01 5256.83  170.45 5261.76  170.77 5266.83  171.16 5271.89  171.19
 5276.83  171.54 5282.01  172.07 5286.84  172.09 5292.13  172.21 5296.84  172.46
 5302.26  172.73 5306.84  172.89 5312.38  173.39 5316.84  173.51  5322.5  173.37
 5326.84   173.5 5332.62   173.6 5336.84  173.81 5342.75  174.04 5346.85  174.22
 5352.87  174.63 5356.85   174.7 5362.99  174.85 5366.85  174.97 5367.84     175
 5374.37  175.18 5378.92  175.31  5390.3  175.71 5391.21  175.75 5391.57  175.76
  5403.5  175.99 5408.77  176.15 5415.79  176.29 5425.98  176.87 5428.08  176.97
 5433.36  177.07 5440.38   177.1 5443.18  177.13 5452.67  176.92 5460.38  177.05
 5464.96  177.27 5476.43  177.37 5477.25  177.39 5477.58   177.4 5489.55  178.05
 5494.78  178.21 5501.84  178.33 5511.98  178.79 5514.13  178.91  5519.5  179.16
 5526.42  179.51 5529.19  179.56 5538.71   179.9 5546.39  180.17 5551.01  180.31
 5562.57  180.79  5563.3  180.83 5563.59  180.83 5575.59  181.11 5580.79   181.3
 5587.88  181.58  5592.1  181.67 5597.99   182.2 5599.27   182.3 5600.17  182.37
 5605.64  182.55 5612.47  182.83 5615.19  182.99 5624.76  183.68  5632.4  183.99
 5637.05   184.1 5648.71  184.73 5649.34  184.76  5649.6  184.76 5661.64   184.7
  5666.8  184.63 5673.93  184.89 5678.13     185
BR D #Mann= 3
 4735.44     .09 5025.84     .05 5047.27     .09
BR D Banks=5025.84,5047.27
BC Design=,, 0 ,, 0 ,,,,,,
BC Use User HTab Curves=0
BC User HTab FreeFlow(D)= 0

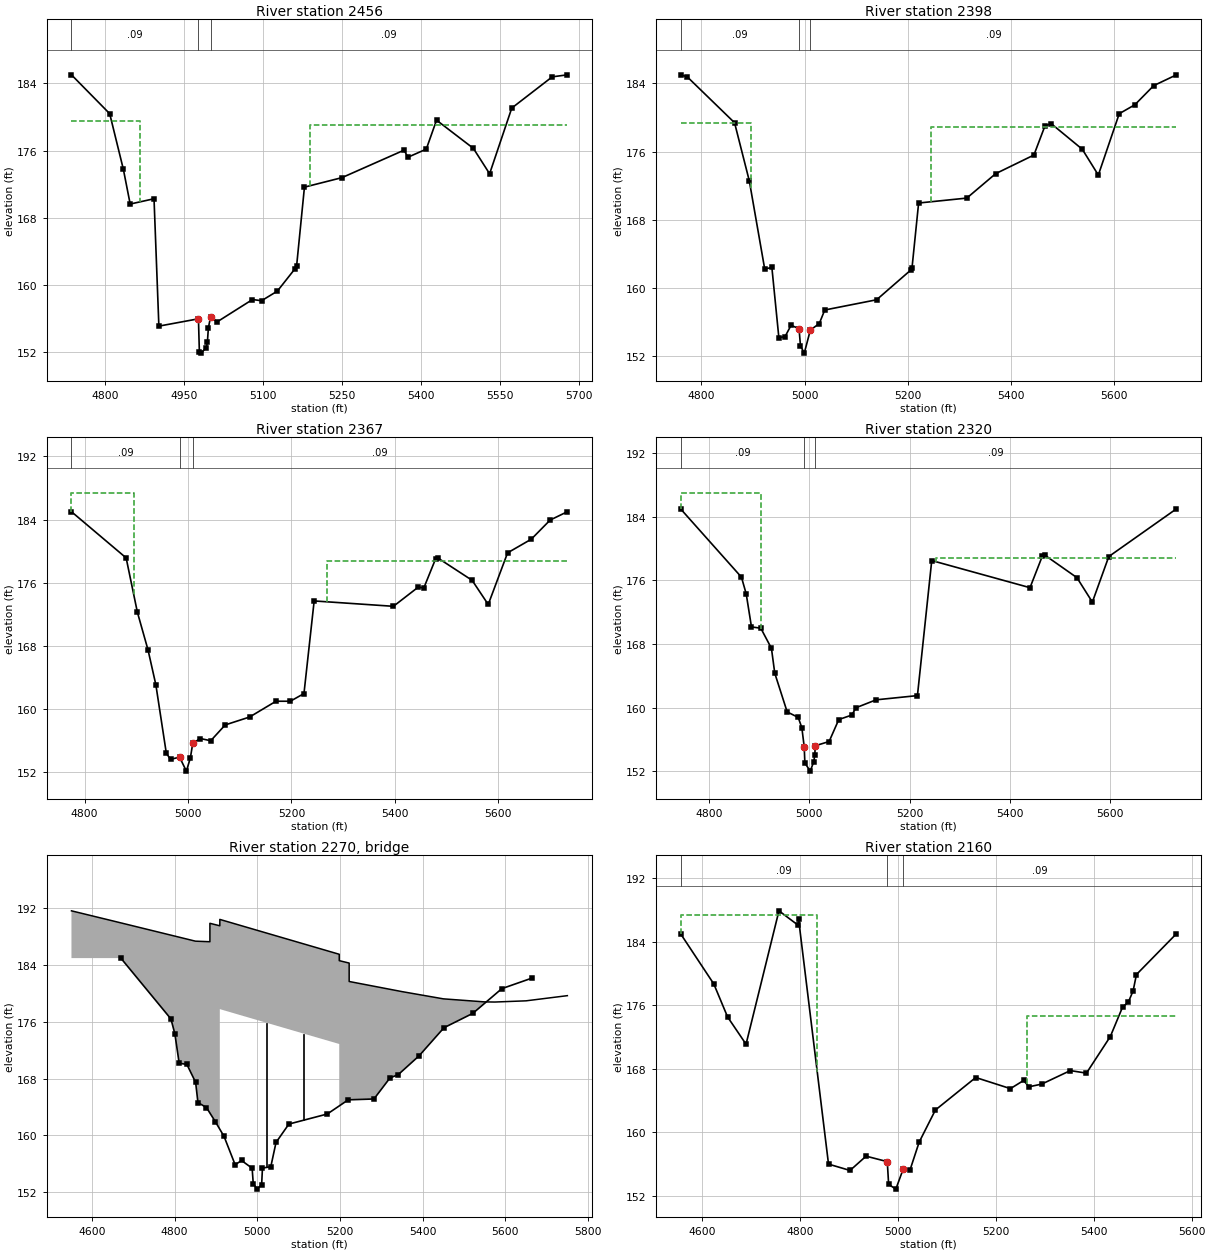
Type RM Length L Ch R = 1 ,2456    ,42.13,57.86,38.29
BEGIN DESCRIPTION:
Downstream NC 540
END DESCRIPTION:
XS GIS Cut Line= 5
    2146208.9537     721571.9662    2146197.2351      721802.771
    2146168.5301     721829.6033    2146164.1891     722191.5808
     2145983.788     722444.0353
#Sta/Elev= 30
 4735.44     185 4808.13  180.38 4834.13  173.76 4847.06  169.64 4892.38  170.27
 4901.61  155.13 4976.85     156  4978.6  152.02 4981.97  151.92 4991.67  152.57
 4993.83  153.21 4995.68   154.9 4999.79  156.21 5012.48  155.64 5079.54  158.29
  5096.8  158.15 5126.81  159.29 5160.53  161.96 5163.37  162.24 5178.33  171.65
 5249.67  172.78 5367.84  176.05 5374.91   175.2 5409.95  176.17 5429.44  179.61
 5499.44  176.26 5530.34  173.24 5572.46  181.05 5649.34  184.76 5678.13     185
#Mann= 3 ,0,0
 4735.44     .09       0 4976.85     .05       0 4999.79     .09       0
#XS Ineff= 2 , 0
       0  4865.1  179.56    5188       0     179
Permanent Ineff=
       F       F
Bank Sta=4976.85,4999.79
XS Rating Curve= 0 ,0
Exp/Cntr=0.5,0.3

Type RM Length L Ch R = 1 ,2398    ,27.95,31.08,32.67
XS GIS Cut Line= 5
    2146183.2245     721537.6888    2146170.3402     721714.0857
    2146134.4481     721814.5992    2146157.3332     722184.8133
     2145984.022     722436.9696
#Sta/Elev= 30
 4759.93     185  4772.8  184.77 4864.51  179.38 4893.13  172.55 4922.91  162.22
  4936.8   162.4 4950.34  154.16 4962.31  154.29 4973.94  155.61 4989.42  155.23
 4992.19   153.2 4999.58  152.35 5011.27  155.05 5028.61  155.82 5039.23  157.41
 5139.68  158.61 5205.74  162.09 5208.18  162.32 5221.02  169.96 5314.39  170.54
 5370.14   173.4 5444.32  175.59 5465.62  178.99 5477.68  179.28 5537.99  176.27
  5569.1  173.24 5609.59  180.44  5639.9  181.49 5676.31  183.73 5720.42     185
#Mann= 3 ,0,0
 4759.93     .09       0 4989.42     .05       0 5011.27     .09       0
#XS Ineff= 2 , 0
       0  4895.7   179.4  5244.1       0   178.9
Permanent Ineff=
       F       F
Bank Sta=4989.42,5011.27
XS Rating Curve= 0 ,0
Exp/Cntr=0.5,0.3

Type RM Length L Ch R = 1 ,2367    ,54.77,46.55,35.79
XS GIS Cut Line= 5
    2146183.1951     721536.4804    2146134.5129     721734.6518
    2146105.8556     721793.2239    2146150.3912     722184.8623
    2145982.9424     722428.0481
#Sta/Elev= 30
 4774.77     185 4880.47  179.15 4902.22  172.27 4922.85  167.48 4937.94  163.08
 4958.14  154.42 4966.24  153.64  4983.8  153.92 4996.91  152.15 5004.61  153.81
 5009.24  155.67  5023.7  156.28 5044.04     156    5072     158 5119.11     159
 5170.19     161 5197.86     161 5224.25  161.97 5243.96   173.7 5397.21  173.02
 5445.16  175.45 5455.94  175.34 5478.73  179.03 5483.33  179.13 5549.35  176.31
 5580.49  173.25 5617.88  179.79 5663.73  181.52 5700.16  183.94 5733.46     185
#Mann= 3 ,0,0
 4774.77     .09       0  4983.8     .05       0 5009.24     .09       0
#XS Ineff= 2 , 0
          4896.3  187.39  5269.4          178.82
Permanent Ineff=
       F       F
Bank Sta=4983.8,5009.24
XS Rating Curve= 0 ,0
Exp/Cntr=0.5,0.3

Type RM Length L Ch R = 1 ,2320    ,205.66,160.68,149.61
BEGIN DESCRIPTION:
Upstream Y29RPA
END DESCRIPTION:
XS GIS Cut Line= 5
    2146183.1592     721535.0024    2146077.9739     721655.3242
    2146083.7517     721832.7586    2146140.2657     722186.8835
    2145974.2538     722426.7355
#Sta/Elev= 30
 4743.94     185 4865.25  176.41  4874.7  174.31 4885.18  170.16 4903.76     170
 4924.94  167.47 4931.56  164.35 4956.28  159.48 4978.25  158.79 4985.51  157.49
 4990.22   155.1 4991.53  153.06 5002.25  152.04 5009.31  153.24 5011.28  154.07
 5012.25  155.23 5039.82  155.76 5059.06  158.52 5085.15  159.09  5093.2     160
 5133.37     161 5215.71  161.53 5244.22   178.5 5439.89  175.09 5464.66  179.09
 5469.22  179.19 5533.38  176.35 5564.11  173.28 5596.81     179 5731.59     185
#Mann= 3 ,0,0
 4743.94     .09       0 4990.22     .05       0 5012.25     .09       0
#XS Ineff= 2 , 0
          4904.5  187.01  5253.6          178.82
Permanent Ineff=
       F       F
Bank Sta=4990.22,5012.25
XS Rating Curve= 0 ,0
Exp/Cntr=0.5,0.3

Type RM Length L Ch R = 3 ,2270    ,,,
BEGIN DESCRIPTION:
Y29RPA
END DESCRIPTION:
Bridge Culvert--1,0,-1,-1, 0
Deck Dist Width WeirC Skew NumUp NumDn MinLoCord MaxHiCord MaxSubmerge Is_Ogee
40.5,40.1,2.6,0, 18, 18, , , 0.98, 0, 2,2,,
  4550.5  4650.5  4750.5  4850.5  4885.5  4885.5  4909.5  4909.5  5198.5  5198.5
  5222.5  5222.5  5350.5  5450.5  5550.5 5574.93  5650.5  5750.5
  191.67  190.25  188.82  187.39  187.31  189.91  189.56  190.46  185.54  184.64
   184.3   181.7  180.27  179.25  178.82   178.8  178.97   179.7
                                                           177.8  172.88
                                                                
  4550.5  4650.5  4750.5  4850.5  4885.5  4885.5  4909.5  4909.5  5198.5  5198.5
  5222.5  5222.5  5350.5  5450.5  5550.5 5574.93  5650.5  5750.5
  191.67  190.25  188.82  187.39  187.31  189.91  189.56  190.46  185.54  184.64
   184.3   181.7  180.27  179.25  178.82   178.8  178.97   179.7
                                                           177.8  172.88
                                                                
Pier Skew, UpSta & Num, DnSta & Num=  ,5022.7, 2 ,5022.7, 2 , 0 , 0 , 0 ,,
     3.5     3.5
     150  178.82
     3.5     3.5
     150  178.82
Pier Skew, UpSta & Num, DnSta & Num=  ,5111.6, 2 ,5111.6, 2 , 0 , 0 , 0 ,,
     3.5     3.5
     150  178.82
     3.5     3.5
     150  178.82
Abutment Skew #Up #Dn= , 5 , 5
  4909.5 4912.13 4912.13 4913.73 4988.73
   177.8   177.8   174.8   174.8   124.8
  4909.5 4912.13 4912.13 4913.73 4988.73
   177.8   177.8   174.8   174.8   124.8
Abutment Skew #Up #Dn= , 5 , 5
 5119.28 5194.28 5195.88 5195.88  5198.5
  119.88  169.88  169.88  172.89  172.88
 5119.28 5194.28 5195.88 5195.88  5198.5
  119.88  169.88  169.88  172.89  172.88
BR Coef=-1 , 1 , 0 ,, 0 ,,,0.8,0,1.2,0,
WSPro=,,,, 1 ,,,, 0 ,,,, 0 ,,,,-1 ,-1 ,-1 , 0 , 0 , 0 , 0 , 0
BR U #Sta/Elev= 30
 4669.94     185 4791.25  176.41  4800.7  174.31 4811.18  170.16 4829.76     170
 4850.94  167.47 4856.56  164.62 4877.19  163.91 4898.51  161.93 4919.74  159.84
 4946.59  155.84 4962.07  156.44  4987.7  155.35 4990.42  153.17 5000.09   152.4
 5010.69  153.03  5012.7  155.37 5032.85  155.56 5045.53  158.99  5076.6  161.58
 5169.55     163 5220.26     165 5282.52  165.12 5321.24  168.09 5341.39  168.56
 5391.67  171.21 5451.84  175.17 5521.91  177.21 5591.93  180.69 5665.49  182.19
BR U #Mann= 3
 4669.94     .09  4987.7     .05  5012.7     .09
BR U Banks=4987.7,5012.7
BR D #Sta/Elev= 30
 4669.94     185 4791.25  176.41  4800.7  174.31 4811.18  170.16 4829.76     170
 4850.94  167.47 4856.56  164.62 4877.19  163.91 4898.51  161.93 4919.74  159.84
 4946.59  155.84 4962.07  156.44 4989.81  155.33 4991.15   154.8 4992.49  153.41
 5001.47  152.51 5012.78  153.12 5014.68  155.33 5032.85  155.56 5045.53  158.99
  5076.6  161.58 5169.55     163 5220.26     165 5282.52  165.12 5321.24  168.09
 5391.67  171.21 5451.84  175.17 5521.91  177.21 5591.93  180.69 5665.49  182.19
BR D #Mann= 3
 4669.94     .09 4989.81     .05 5014.68     .09
BR D Banks=4989.81,5014.68
BC Design=,, 0 ,, 0 ,,,,,,
BC Use User HTab Curves=0
BC User HTab FreeFlow(D)= 0

Type RM Length L Ch R = 1 ,2160    ,37.12,115.18,131.66
BEGIN DESCRIPTION:
Downstream Y29RPA
END DESCRIPTION:
XS GIS Cut Line= 4
     2146168.594     721497.7175    2145891.1636     721617.7107
    2145942.0606     721838.8593    2145668.7487     722238.1953
#Sta/Elev= 30
 4555.87     185 4623.85  178.67 4651.98  174.52 4689.67  171.09 4756.91  187.88
 4795.62  186.09 4797.05  186.81 4858.14     156 4902.08   155.2  4934.9     157
 4978.21  156.31 4980.97  153.45 4995.67  152.85 5011.08  155.44 5024.66  155.26
 5043.36  158.77 5076.54  162.81  5158.9   166.9  5229.8   165.5 5256.78  166.53
 5267.59  165.73  5293.7  166.07 5352.13  167.77 5385.09  167.45 5433.89  172.06
 5458.91  175.77 5470.69  176.39 5480.45  177.81 5487.21  179.86 5568.98     185
#Mann= 3 ,0,0
 4555.87     .09       0 4978.21     .05       0 5011.08     .09       0
#XS Ineff= 2 , 0
       0  4835.1  187.39  5263.3       0   174.6
Permanent Ineff=
       F       F
Bank Sta=4978.21,5011.08
XS Rating Curve= 0 ,0
Exp/Cntr=0.5,0.3

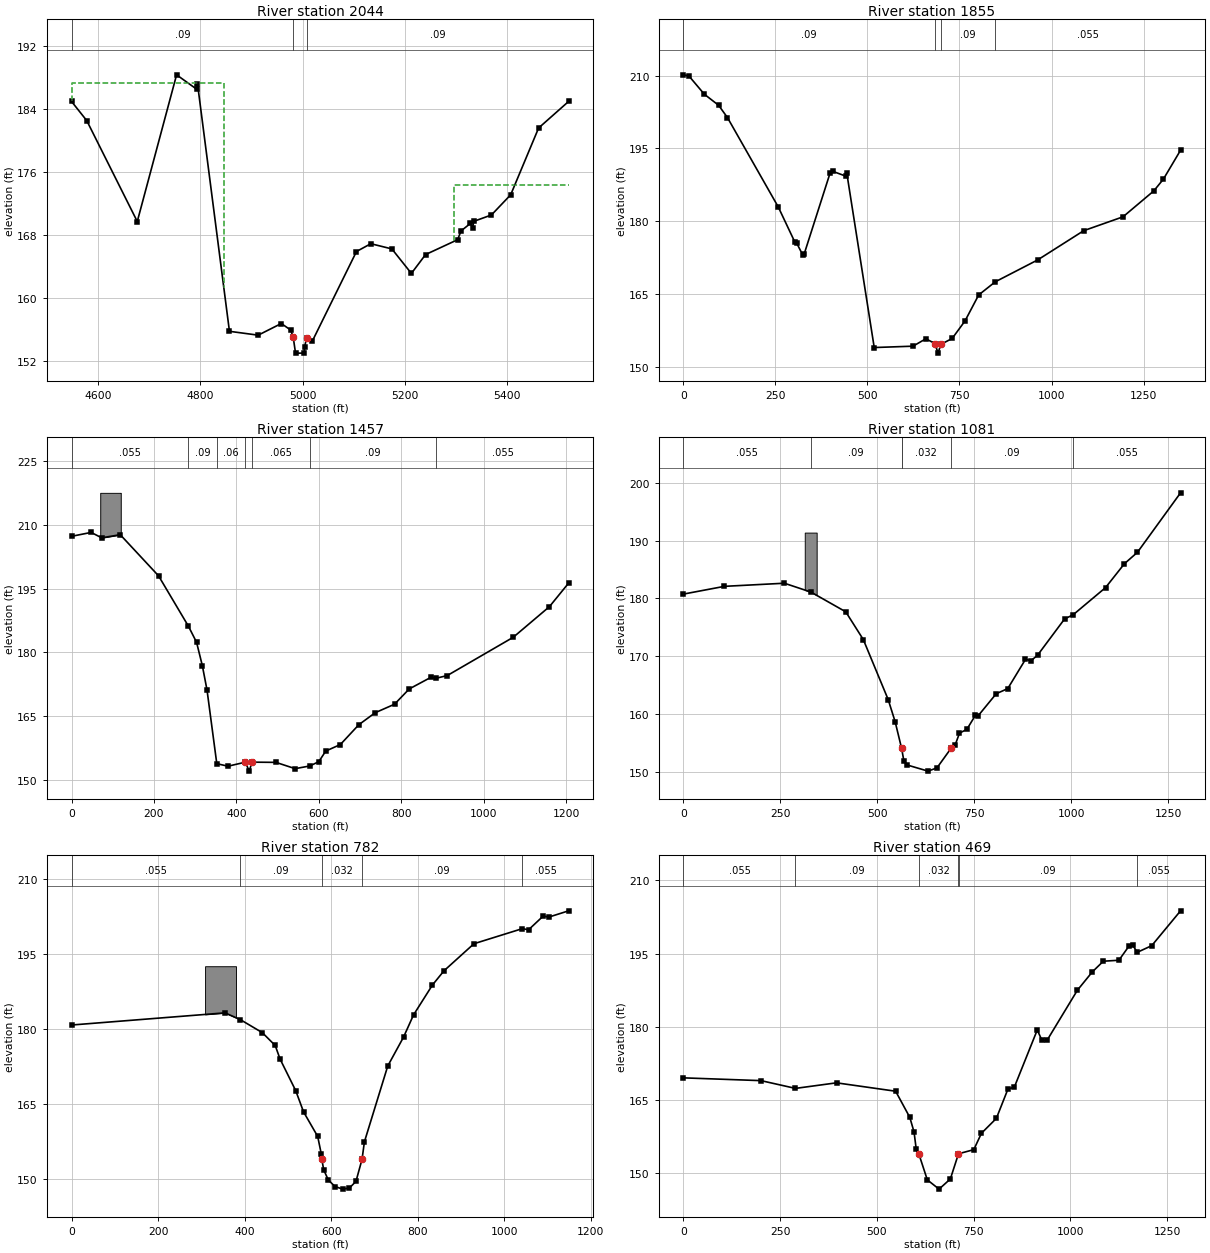
Type RM Length L Ch R = 1 ,2044    ,129.53,189.35,207.74
XS GIS Cut Line= 3
     2146157.513     721460.4359    2145875.9067      721587.631
     2145661.187     722214.6296
#Sta/Elev= 30
 4548.37     185 4578.13  182.57  4676.9  169.76 4753.76  188.38 4793.16  186.55
  4794.6  187.27  4857.1  155.82 4913.28  155.33 4958.51  156.81 4977.03  155.97
 4981.81  155.04  4986.3  153.05 5003.62  153.05 5003.95  153.86 5008.26  155.03
 5018.78  154.53 5105.43  165.95 5133.48  166.94 5174.61  166.28 5212.76  163.17
 5240.46  165.56 5303.14  167.45  5309.8  168.56 5328.22  169.52 5332.33  168.96
 5334.78  169.78 5369.27  170.59 5406.87  173.15 5461.48  181.63 5520.12     185
#Mann= 3 ,0,0
 4548.37     .09       0 4981.81     .05       0 5008.26     .09       0
#XS Ineff= 2 , 0
       0  4846.1  187.39  5295.7       0   174.4
Permanent Ineff=
       F       F
Bank Sta=4981.81,5008.26
XS Rating Curve= 0 ,0
Exp/Cntr=0.5,0.3

Type RM Length L Ch R = 1 ,1855    ,359.89,398.72,297.29
XS GIS Cut Line= 2
2146192.77551657721126.7807490832145206.96859962722050.073351085
#Sta/Elev= 30
       0  210.14   14.73  209.91   56.63  206.15    95.4  203.88  119.43  201.35
  257.64  182.94  302.79   175.7  307.46  175.53  324.47  173.02  327.91  173.26
   398.2   189.9  406.58  190.26  442.16  189.26  443.66  189.97   518.3  154.03
  623.69  154.31  658.51  155.83   683.3  154.86  691.69  152.88  699.29  154.69
     730  155.89  764.95   159.5  802.13  164.85  847.13  167.55   962.3  172.05
 1087.45  178.07 1194.38  180.93 1277.97  186.26 1304.05  188.68 1350.66  194.63
#Mann= 4 ,-1,0
       0     .09       0   683.3     .05       0  699.29     .09       0
  847.13    .055       0
Bank Sta=683.3,699.29
XS Rating Curve= 0 ,0
Exp/Cntr=0.3,0.1

Type RM Length L Ch R = 1 ,1457    ,404.45,375.18,230.5
XS GIS Cut Line= 3
2145776.81272846720972.8987572792145529.15926415 721242.19224298
2145156.47586757721994.771725416
#Sta/Elev= 30
       0  207.31   47.52  208.23   73.21  206.96  118.21  207.69  211.09  198.02
  283.57  186.17   303.3  182.39  317.28   176.9  328.68  171.16  352.35  153.85
   379.7  153.26  421.83  154.21  430.81   152.1  438.01  154.21  495.82  154.16
  542.34  152.68  578.23  153.32  599.79  154.33  616.64  156.82  652.03  158.35
  696.95  163.02  736.46  165.83   783.4  167.83  819.06  171.42  871.56  174.15
  885.19  173.96  911.31  174.57 1071.49  183.58 1159.17  190.78 1205.66  196.31
#Mann= 7 ,-1,0
       0    .055       0  283.57     .09       0  352.35     .06       0
  421.83     .05       0  438.01    .065       0  578.23     .09       0
  885.19    .055       0
#Block Obstruct= 1 ,-1
   69.62  119.46 217.539
Bank Sta=421.83,438.01
XS Rating Curve= 0 ,0
Exp/Cntr=0.3,0.1

Type RM Length L Ch R = 1 ,1081    ,248.49,299.75,317.33
XS GIS Cut Line= 4
2145259.86512738720797.3767441512145077.13042486720996.942574382
2145243.03465074721598.0445117952145096.36534828 721956.30122745
#Sta/Elev= 30
       0  180.73  105.56  182.07  260.04  182.61  328.52  181.08  418.31  177.66
  463.58  172.85  527.64  162.47  545.65  158.62  562.32     154  567.94  151.91
  575.69  151.16  630.33  150.08  653.36  150.64  689.39     154  700.05  154.57
  711.45  156.65  730.49  157.32  752.29  159.72  758.35  159.56  806.14  163.48
  835.88  164.37  881.56  169.43  896.09  169.21  912.58  170.14  982.39  176.43
 1004.27  177.14 1087.89  181.85 1136.75     186 1170.08  187.96 1281.28  198.26
#Mann= 6 ,-1,0
       0    .055       0  328.52     .09       0  562.23    .032       0
  562.32    .032       0  689.39     .09       0 1004.27    .055       0
#Block Obstruct= 1 ,-1
  312.59   343.3 191.376
Bank Sta=562.32,689.39
XS Rating Curve= 0 ,0
Exp/Cntr=0.3,0.1

Type RM Length L Ch R = 1 ,782     ,309.42,312.87,256.59
XS GIS Cut Line= 5
2145246.34019542720801.2838888172144996.88323319721068.774527729
2144912.61886394721279.5923616892144854.76174039721547.639024794
  2144897.701267721826.162903786
#Sta/Elev= 30
       0  180.82  354.86  183.25  390.49  181.88  440.89   179.3  470.75  176.73
  481.94  174.03  518.15  167.71  536.26  163.47  568.93  158.57  577.31  155.04
  578.46     154  582.85  151.89  593.45  149.87  608.92  148.56  626.85  148.04
   642.3  148.27  657.41  149.59  671.42     154  676.92  157.49  730.87  172.64
  767.37  178.41  790.38  182.83  834.01   188.8  860.79  191.65  930.11  197.06
 1041.87  200.07 1056.35  199.85 1090.31   202.6 1102.76  202.37 1148.83  203.63
#Mann= 5 ,-1,0
       0    .055       0  390.49     .09       0  578.46    .032       0
  671.42     .09       0 1041.87    .055       0
#Block Obstruct= 1 ,-1
  308.66  380.04 192.566
Bank Sta=578.46,671.42
XS Rating Curve= 0 ,0
Exp/Cntr=0.3,0.1

Type RM Length L Ch R = 1 ,469     ,352.7,376.95,391.55
XS GIS Cut Line= 5
 2144816.5529775720635.9812629822144657.26049203720996.642425418
2144608.04388124721273.7091823222144708.58270288721491.858853698
2144882.67363721721817.146065474
#Sta/Elev= 30
       0  169.54  200.42  168.97  289.47  167.38  395.55  168.52  548.38   166.8
  585.01  161.44  595.96  158.44  601.66  154.88  608.09  154.01  630.25  148.63
   660.6  146.73  689.77  148.81  710.85  153.98  750.35  154.82  770.23  158.19
  808.71  161.23  838.66  167.25  855.14  167.63  914.41  179.35  926.76   177.2
   939.7  177.23 1018.21  187.51  1056.7  191.26 1085.16  193.45 1125.43  193.65
 1151.52  196.55 1161.37  196.74 1172.79  195.27 1210.27  196.64 1284.82  203.78
#Mann= 6 ,-1,0
       0    .055       0  289.47     .09       0  608.09    .032       0
  710.85    .032       0  710.89     .09       0 1172.79    .055       0
Bank Sta=608.09,710.85
XS Rating Curve= 0 ,0
Exp/Cntr=0.3,0.1

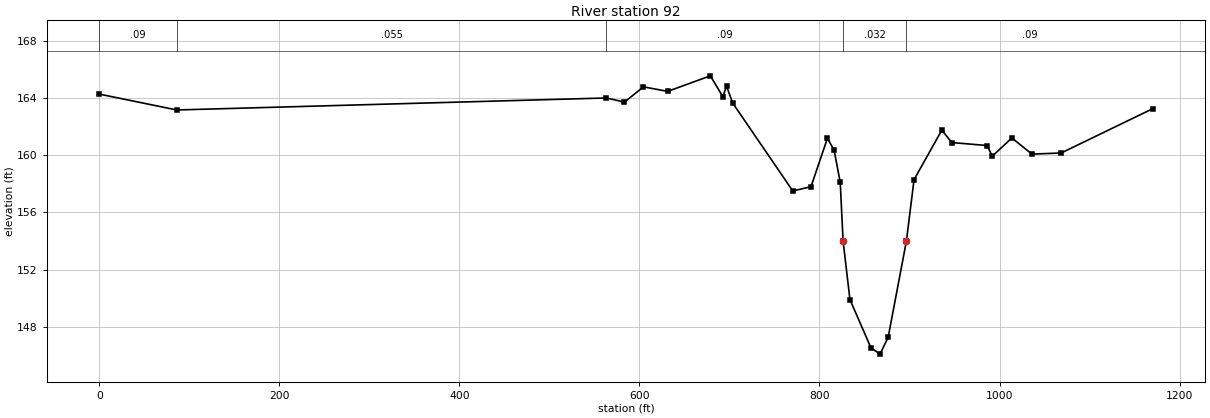
Type RM Length L Ch R = 1 ,92      ,30.56,91.89,82.6
XS GIS Cut Line= 6
2144461.90260649720473.6833817362144338.67682326721122.873604417
2144284.05297428721179.6063088772144276.44963551721213.823286414
2144253.63766611 721376.545022192144256.67952245721606.940899909
#Sta/Elev= 30
       0  164.28   86.01  163.17  563.24  164.01  583.37  163.72  604.49  164.79
  631.33  164.47  678.81  165.56  692.66   164.1  696.76  164.84  703.63  163.65
  770.38   157.5   790.6   157.8  808.84  161.19  816.25  160.36  823.07   158.1
  826.24     154  833.84   149.9  857.14  146.53  867.27  146.08  876.32  147.26
   896.6     154  905.06  158.29  935.95  161.76  946.97  160.89  986.38  160.68
  991.91  159.93 1013.72  161.21 1036.08  160.08 1068.54  160.16 1170.24  163.26
#Mann= 5 ,-1,0
       0     .09       0   86.01    .055       0  563.24     .09       0
  826.24    .032       0   896.6     .09       0
Bank Sta=826.24,896.6
XS Rating Curve= 0 ,0
Exp/Cntr=0.3,0.1
LCMann Table=0

Chan Stop Cuts=-1
Use User Specified Reach Order=0
Composite Channel Slope=5

--- R-2829B_Basin15_Strm7_NC540.g01 (geometry) ---

Geom Title=Duplicate Effective
Program Version=6.20

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
River Reach=Basin15 Stream7 ,Main

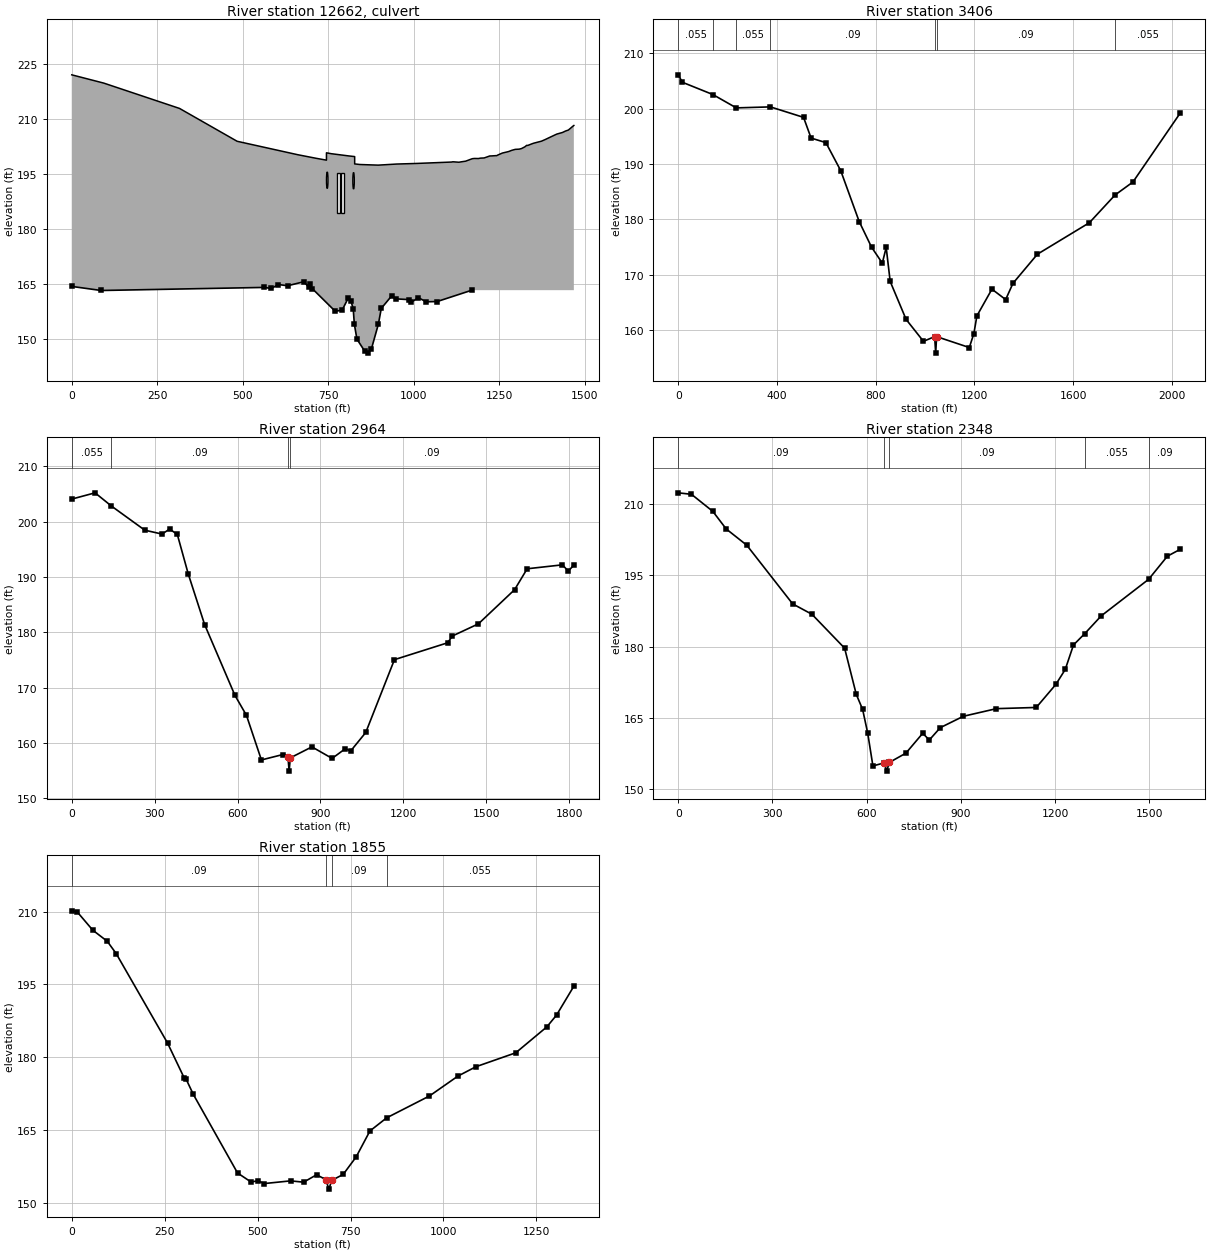
Type RM Length L Ch R = 2 ,12662   ,,,
BEGIN DESCRIPTION:
Poole Road
deck includes 2' tall guardrail (see STR_120PHT1.JPG)
END DESCRIPTION:
Bridge Culvert--1,0,-1,-1, 0
Deck Dist Width WeirC Skew NumUp NumDn MinLoCord MaxHiCord MaxSubmerge Is_Ogee
57,41,2.6,0, 60, 60, , , 0.98, 0, 1,1,,
       0   93.71  315.15   483.5 660.432 714.846  744.75  744.75 758.908 810.069
  827.25  827.25 842.475 896.069 950.7961008.932 1110.24 1112.37    1115 1132.08
 1140.12 1151.73 1168.93 1171.51 1177.13 1189.07 1195.01 1205.81 1219.85 1222.29
 1227.09 1240.15 1242.52 1244.94 1258.93 1264.48 1270.55 1277.78 1286.37 1296.32
 1296.82 1308.15 1315.05 1325.04 1330.19 1333.23 1346.79 1351.95 1354.23 1373.55
 1385.25 1395.32 1416.74 1417.29  1418.6 1434.88 1443.96 1452.09 1466.39 1468.14
  222.02  219.76  212.85  203.89  200.23  199.24  198.74  200.74   200.5  199.89
  199.71  197.71  197.55  197.38  197.68  197.84  198.22  198.26  198.29  198.17
   198.3  198.46  199.06  199.14   199.2  199.18  199.29  199.34   199.8  199.88
  199.89  199.97  199.96   200.1  200.67   200.8  200.93   201.1  201.41  201.67
  201.68  201.74   201.9  202.38  202.78  202.75  203.24   203.4  203.45  203.92
   204.4  204.85  205.79  205.81  205.86  206.29  206.69  206.95  208.08  208.19
                                                                                
                                                                                
                                                                                
                                                                                
                                                                                
                                                                                
       0   93.71  315.15   483.5 660.432 714.846  744.75  744.75 758.908 810.069
  827.25  827.25 842.475 896.069 950.7961008.932 1110.24 1112.37    1115 1132.08
 1140.12 1151.73 1168.93 1171.51 1177.13 1189.07 1195.01 1205.81 1219.85 1222.29
 1227.09 1240.15 1242.52 1244.94 1258.93 1264.48 1270.55 1277.78 1286.37 1296.32
 1296.82 1308.15 1315.05 1325.04 1330.19 1333.23 1346.79 1351.95 1354.23 1373.55
 1385.25 1395.32 1416.74 1417.29  1418.6 1434.88 1443.96 1452.09 1466.39 1468.14
  222.02  219.76  212.85  203.89  200.23  199.24  198.74  200.74   200.5  199.89
  199.71  197.71  197.55  197.38  197.68  197.84  198.22  198.26  198.29  198.17
   198.3  198.46  199.06  199.14   199.2  199.18  199.29  199.34   199.8  199.88
  199.89  199.97  199.96   200.1  200.67   200.8  200.93   201.1  201.41  201.67
  201.68  201.74   201.9  202.38  202.78  202.75  203.24   203.4  203.45  203.92
   204.4  204.85  205.79  205.81  205.86  206.29  206.69  206.95  208.08  208.19
                                                                                
                                                                                
                                                                                
                                                                                
                                                                                
                                                                                
BR Coef=-1 , 1 , 0 ,1.25, 0 ,,,0.8,0,2,0,
WSPro=,,,, 1 ,,,, 0 ,,,, 0 ,,,,-1 ,-1 ,-1 , 0 , 0 , 0 , 0 , 0
Culvert=1,4.5,,68.3,0.012,0.2,1,1,2,191.01,747,189.84,748,Culvert #1  , 0 ,49
     747     748
BC Culvert Barrel=1,,0
Culvert Bottom n=0.012
Culvert=2,11,10,52.3,0.012,0.4,1,8,1,184.23,780,183.21,781,Culvert #2  , 0 ,52
     780     781
BC Culvert Barrel=1,,0
Culvert Bottom n=0.05
Culvert Bottom Depth=3
Culvert Depth Blocked=3
Culvert=2,11,10,52.3,0.012,0.4,1,8,1,184.23,791,183.21,792,Culvert #3  , 0 ,52
     791     792
BC Culvert Barrel=1,,0
Culvert Bottom n=0.05
Culvert Bottom Depth=1
Culvert Depth Blocked=1
Culvert=1,4.5,,61,0.012,0.2,1,1,2,190.86,824,189.77,825,Culvert #4  , 0 ,49
     824     825
BC Culvert Barrel=1,,0
Culvert Bottom n=0.012
BC Design=,, 0 ,, 0 ,,,,,,
BC Use User HTab Curves=0
BC User HTab FreeFlow(D)= 0

Type RM Length L Ch R = 1 ,3406    ,380.43,442.04,299.61
XS GIS Cut Line= 6
2147617.68728983722583.5512799022147142.81718248722406.226419926
2146893.35956913722252.9453770522146691.99089217 722243.92853874
2146439.52788311722343.1105049252146202.09250385723067.438225567
#Sta/Elev= 30
       0  206.11   16.61  204.77   140.4  202.55  235.42  200.14  373.58  200.32
  507.86  198.43  538.43  194.69  598.36  193.87  658.38  188.82  733.34  179.62
  783.24  175.01  827.05  172.11  842.78  174.94  858.98   168.8  923.46  161.95
  993.82  157.99 1039.11  158.84  1043.4  155.86 1047.07  158.84 1179.63  156.87
 1198.14   159.4 1210.41  162.59 1271.29  167.41 1326.94  165.53  1356.6  168.47
 1455.54  173.72 1666.33  179.41 1770.23  184.41 1842.83  186.76 2034.75  199.23
#Mann= 7 ,-1,0
       0    .055       0   140.4     .09       0  235.42    .055       0
  373.58     .09       0 1039.11     .05       0 1047.07     .09       0
 1770.23    .055       0
#XS Ineff= 2 , 0
                         1271.85          167.12
Permanent Ineff=
       F       F
Bank Sta=1039.11,1047.07
XS Rating Curve= 0 ,0
Exp/Cntr=0.3,0.1

Type RM Length L Ch R = 1 ,2964    ,494.48,616.46,411.57
XS GIS Cut Line= 3
2147169.86639529 721468.507137062146550.73143226721925.344869971
2145748.26081777722598.578909695
#Sta/Elev= 30
       0  204.07   84.29   205.2  143.54  202.81  264.26  198.45  326.67  197.75
  354.03  198.65  381.91  197.69   421.3  190.58  480.76   181.4  590.46  168.61
  632.12     165  686.26  156.94  764.03  157.92  782.54  157.41  786.54  154.92
   790.9  157.32  869.04   159.3  942.16  157.22  990.41  158.99 1009.16  158.55
 1063.83   161.9 1167.65  175.06 1360.44  178.11 1377.12  179.33 1471.56  181.53
 1602.49   187.7 1647.99  191.48 1775.66  192.19 1796.68  191.06 1816.91  192.14
#Mann= 4 ,-1,0
       0    .055       0  143.54     .09       0  782.54     .05       0
   790.9     .09       0
Bank Sta=782.54,790.9
XS Rating Curve= 0 ,0
Exp/Cntr=0.3,0.1

Type RM Length L Ch R = 1 ,2348    ,419.82,492.3,465.48
XS GIS Cut Line= 4
2146397.45038939721149.923468292 2146069.8498823721823.157508075
2145883.50883508721952.3940827852145498.80320448722442.292471051
#Sta/Elev= 30
       0  212.28   42.13  211.97  110.18  208.38  152.63   204.7   218.2  201.28
  364.24  188.96   425.6  186.78  529.68  179.66  566.81  169.95  586.94  166.82
  603.11  161.84  619.76  154.93  655.65  155.57  663.78  153.84  671.87  155.66
  724.72  157.61  778.28  161.78  799.35  160.38  834.29  162.97   907.8  165.36
 1013.04  166.96  1139.8  167.21 1202.21  172.05 1232.04  175.19 1258.31  180.34
 1293.73  182.68 1346.57  186.44 1497.36  194.11 1557.19  198.97 1598.38  200.43
#Mann= 5 ,-1,0
       0     .09       0  655.65     .05       0  671.87     .09       0
 1293.73    .055       0 1497.36     .09       0
Bank Sta=655.65,671.87
XS Rating Curve= 0 ,0
Exp/Cntr=0.3,0.1

Type RM Length L Ch R = 1 ,1855    ,359.89,398.72,297.29
XS GIS Cut Line= 2
2146192.77551657721126.7807490832145206.96859962722050.073351085
#Sta/Elev= 30
       0  210.14   14.73  209.91   56.63  206.15    95.4  203.88  119.43  201.35
  257.64  182.94  302.79   175.7  307.46  175.53  327.13  172.35  445.98   156.2
  482.45  154.34  500.22   154.6   518.3  154.03   588.7  154.58  623.69  154.31
  658.51  155.83   683.3  154.86  691.69  152.88  699.29  154.69     730  155.89
  764.95   159.5  802.13  164.85  847.13  167.55   962.3  172.05 1038.87  176.14
 1087.45  178.07 1194.38  180.93 1277.97  186.26 1304.05  188.68 1350.66  194.63
#Mann= 4 ,-1,0
       0     .09       0   683.3     .05       0  699.29     .09       0
  847.13    .055       0
Bank Sta=683.3,699.29
XS Rating Curve= 0 ,0
Exp/Cntr=0.3,0.1

--- R-2829B_Basin15_Strm7_NC540.g03 (geometry) ---

Geom Title=Corrected Effective
Program Version=6.41

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
River Reach=Basin15 Stream7 ,Main