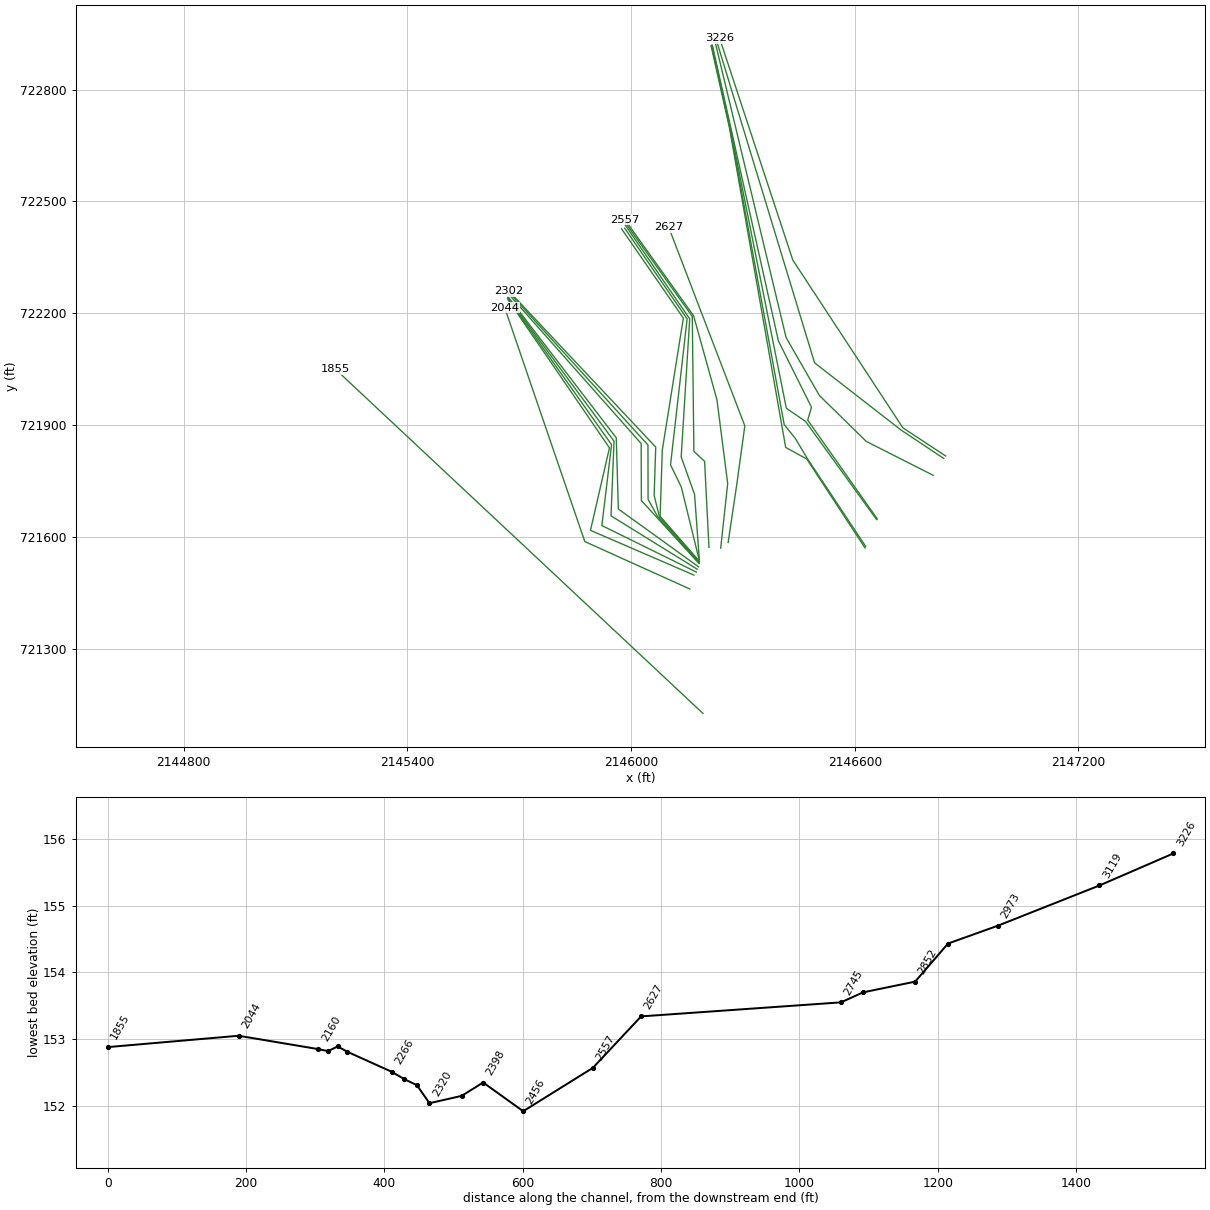
HEC-RAS study R-2829B_Basin15_Strm7_NC540.prj: R-2829B_Basin15_Strm7_I540

--- R-2829B_Basin15_Strm7_NC540.g03 (geometry) --- (continued)

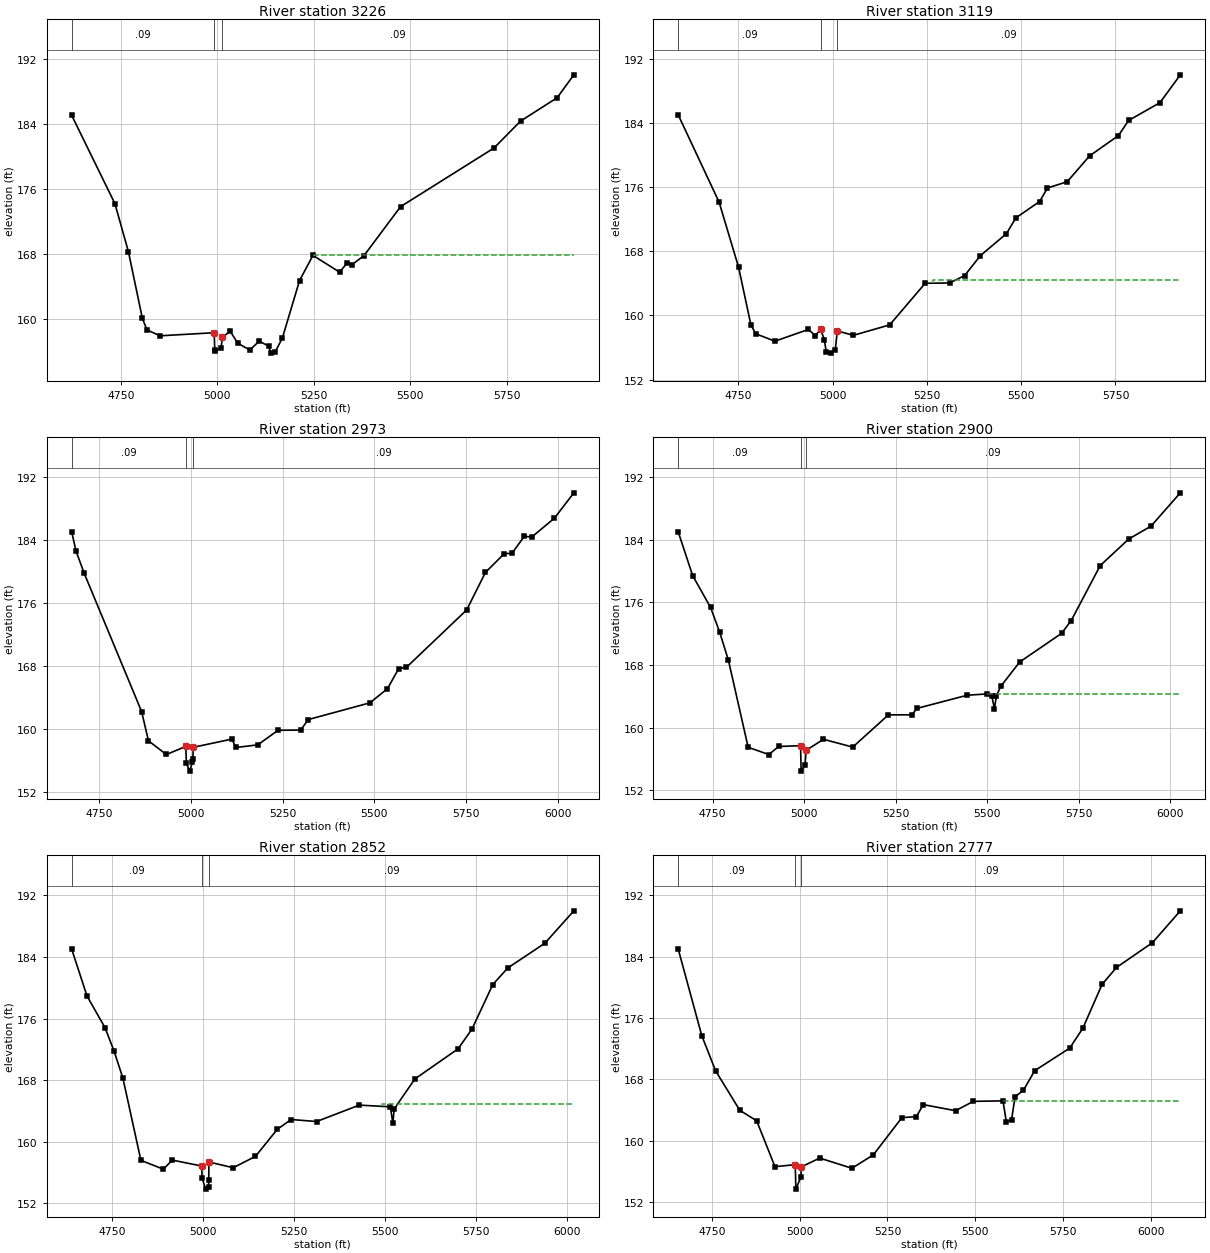
Type RM Length L Ch R = 1 ,3226    ,52.18,106.95,84.48
XS GIS Cut Line= 4
    2146843.9166     721817.1018    2146728.9405     721892.7372
    2146433.8252     722342.6326    2146237.5417     722937.3186
#Sta/Elev= 30
 4622.29     185 4734.16  174.16 4769.27  168.24 4805.15  160.09 4817.11  158.64
 4851.14  157.91 4991.56  158.29 4993.06  156.21 4994.88  156.07 5009.35  156.37
  5012.9  157.74 5033.14  158.47 5052.64     157 5084.05  156.16 5108.22  157.25
 5133.47  156.63 5137.72  155.78 5149.71  155.93 5168.41  157.64    5213  164.71
  5247.7   167.8  5316.9  165.73  5336.6  166.89 5348.49  166.65 5380.09  167.77
 5474.87  173.79 5717.11     181 5786.23  184.32 5880.85  187.18 5924.21     190
#Mann= 3 ,0,0
 4622.29     .09       0 4991.56     .05       0  5012.9     .09       0
#XS Ineff= 2 , 0
                         5249.45          167.86
Permanent Ineff=
       F       F
Bank Sta=4991.56,5012.9
XS Rating Curve= 0 ,0
Exp/Cntr=0.3,0.1

Type RM Length L Ch R = 1 ,3119    ,73.55,146.29,48.98
BEGIN DESCRIPTION:
Upstream Y29RPD
END DESCRIPTION:
XS GIS Cut Line= 4
    2146838.6554     721810.5489    2146724.6658     721886.3471
    2146492.2038     722067.0229    2146230.4001     722927.4661
#Sta/Elev= 30
 4591.14     185 4699.51  174.12 4751.19  165.99 4783.78  158.81 4796.68  157.71
 4847.37  156.79 4936.03  158.25  4954.8  157.47 4968.27  158.29 4978.47  156.97
 4983.39  155.43 4995.65   155.3  5007.5  155.74 5012.76  158.07 5055.23  157.52
 5151.61  158.82  5245.7  164.01 5310.61  164.05 5350.23  164.97 5392.05  167.46
 5460.87  170.19 5486.13  172.17 5548.86   174.2 5569.76  175.89 5622.03  176.67
 5681.34  179.89 5757.93  182.43 5784.81  184.31 5867.93  186.53 5921.84     190
#Mann= 3 ,0,0
 4591.14     .09       0 4968.27     .05       0 5012.76     .09       0
#XS Ineff= 2 , 0
                         5266.61          164.42
Permanent Ineff=
       F       F
Bank Sta=4968.27,5012.76
XS Rating Curve= 0 ,0
Exp/Cntr=0.3,0.1

Type RM Length L Ch R = 1 ,2973    ,80.31,72.63,25.24
XS GIS Cut Line= 5
    2146810.4704     721765.2566    2146630.8257      721856.303
    2146505.1644     721979.3476    2146415.7968      722134.738
    2146226.1235     722924.9498
#Sta/Elev= 30
 4674.79     185 4686.49   182.6 4708.25  179.84  4865.4  162.24 4883.95  158.54
 4932.71  156.81 4985.73  157.83  4987.4  155.69 4996.06   154.7 5003.75   155.8
 5005.28   156.3 5006.04  157.72 5111.15  158.76 5122.69   157.7 5181.92  158.03
 5237.33  159.88 5299.04  159.91 5319.61  161.24 5487.71  163.36  5535.6  165.15
 5566.46  167.71 5587.03  167.85 5751.59  175.14 5803.02  179.91 5854.44   182.3
 5875.01  182.31 5908.99  184.49 5929.05  184.39 5990.92  186.78 6043.97     190
#Mann= 3 ,0,0
 4674.79     .09       0 4985.73     .05       0 5006.04     .09       0
Bank Sta=4985.73,5006.04
XS Rating Curve= 0 ,0
Exp/Cntr=0.3,0.1

Type RM Length L Ch R = 1 ,2900    ,6.07,47.59,29.49
BEGIN DESCRIPTION:
Downstream Y29RPD
END DESCRIPTION:
XS GIS Cut Line= 5
    2146660.4483     721648.3271     2146473.749     721913.2838
    2146483.9778     721947.8159    2146395.2282     722125.7746
     2146218.144     722918.7873
#Sta/Elev= 30
 4656.08     185 4695.48  179.42 4744.42  175.35 4768.89  172.24 4793.36  168.57
 4847.07  157.48 4903.47  156.55  4930.4  157.58 4990.31  157.68 4991.79  154.43
  5002.6   155.2 5005.19  157.08 5052.82   158.5 5132.76   157.5 5230.26  161.62
 5295.26  161.63 5307.44  162.44 5445.46  164.13 5500.34   164.3 5512.67     164
 5519.88  162.42 5525.42  164.09 5537.68   165.3 5588.92  168.38 5703.25  172.04
 5729.64  173.68  5808.8   180.7  5886.6  184.09 5947.58  185.74 6027.63     190
#Mann= 3 ,0,0
 4656.08     .09       0 4990.31     .05       0 5005.19     .09       0
#XS Ineff= 2 , 0
                         5500.24           164.3
Permanent Ineff=
       F       F
Bank Sta=4990.31,5005.19
XS Rating Curve= 0 ,0
Exp/Cntr=0.3,0.1

Type RM Length L Ch R = 1 ,2852    ,47.84,75.14,13.17
XS GIS Cut Line= 5
    2146658.6097     721646.5736    2146467.8954     721909.9545
    2146416.4703     721945.1774    2146266.4026     722695.7562
    2146216.7734     722918.3148
#Sta/Elev= 30
 4638.42     185 4680.35  178.93 4729.74  174.84 4754.65   171.8 4779.13  168.26
 4828.52   157.6 4890.26  156.45 4914.96  157.63 4995.68  156.86  4996.9  155.31
 5006.51  153.86  5014.5  154.18 5015.15  154.99 5015.66  157.38 5082.42  156.64
 5143.61  158.11 5203.56  161.62  5241.8   162.9 5311.85  162.64 5429.19  164.77
 5514.67  164.55 5521.62  162.41  5525.1  164.26 5582.17  168.17 5700.72  172.07
 5738.96  174.62 5796.38  180.42 5837.36  182.57 5939.83   185.8 6019.39     190
#Mann= 3 ,0,0
 4638.42     .09       0 4995.68     .05       0 5015.66     .09       0
#XS Ineff= 2 , 0
                          5490.7          164.95
Permanent Ineff=
       F       F
Bank Sta=4995.68,5015.66
XS Rating Curve= 0 ,0
Exp/Cntr=0.3,0.1

Type RM Length L Ch R = 1 ,2777    ,44.24,32.06,6.42
XS GIS Cut Line= 6
    2146629.2785     721574.6272    2146473.3007     721809.4642
    2146440.7223      721863.973     2146410.718     721901.5015
    2146265.2546     722695.9221    2146215.6968     722917.9437
#Sta/Elev= 30
 4654.58     185 4721.69   173.7 4760.93  169.13 4829.74  163.98 4877.77  162.61
 4929.81  156.63  4987.5  156.89 4989.33   153.7 5003.28  155.24  5005.2  156.61
 5057.24  157.75 5148.77  156.42 5209.77  158.17 5291.11  163.03 5331.78  163.15
 5352.11  164.72 5443.62  163.93 5494.46  165.15 5578.63  165.21 5588.33  162.41
 5603.03  162.75 5613.04  165.76  5636.8  166.59 5668.83  169.15  5768.4  172.09
 5805.74  174.68 5860.52   180.4 5901.51  182.61 6003.98  185.85 6083.16     190
#Mann= 3 ,0,0
 4654.58     .09       0  4987.5     .05       0  5005.2     .09       0
#XS Ineff= 2 , 0
                         5578.62          165.21
Permanent Ineff=
       F       F
Bank Sta=4987.5,5005.2
XS Rating Curve= 0 ,0
Exp/Cntr=0.3,0.1

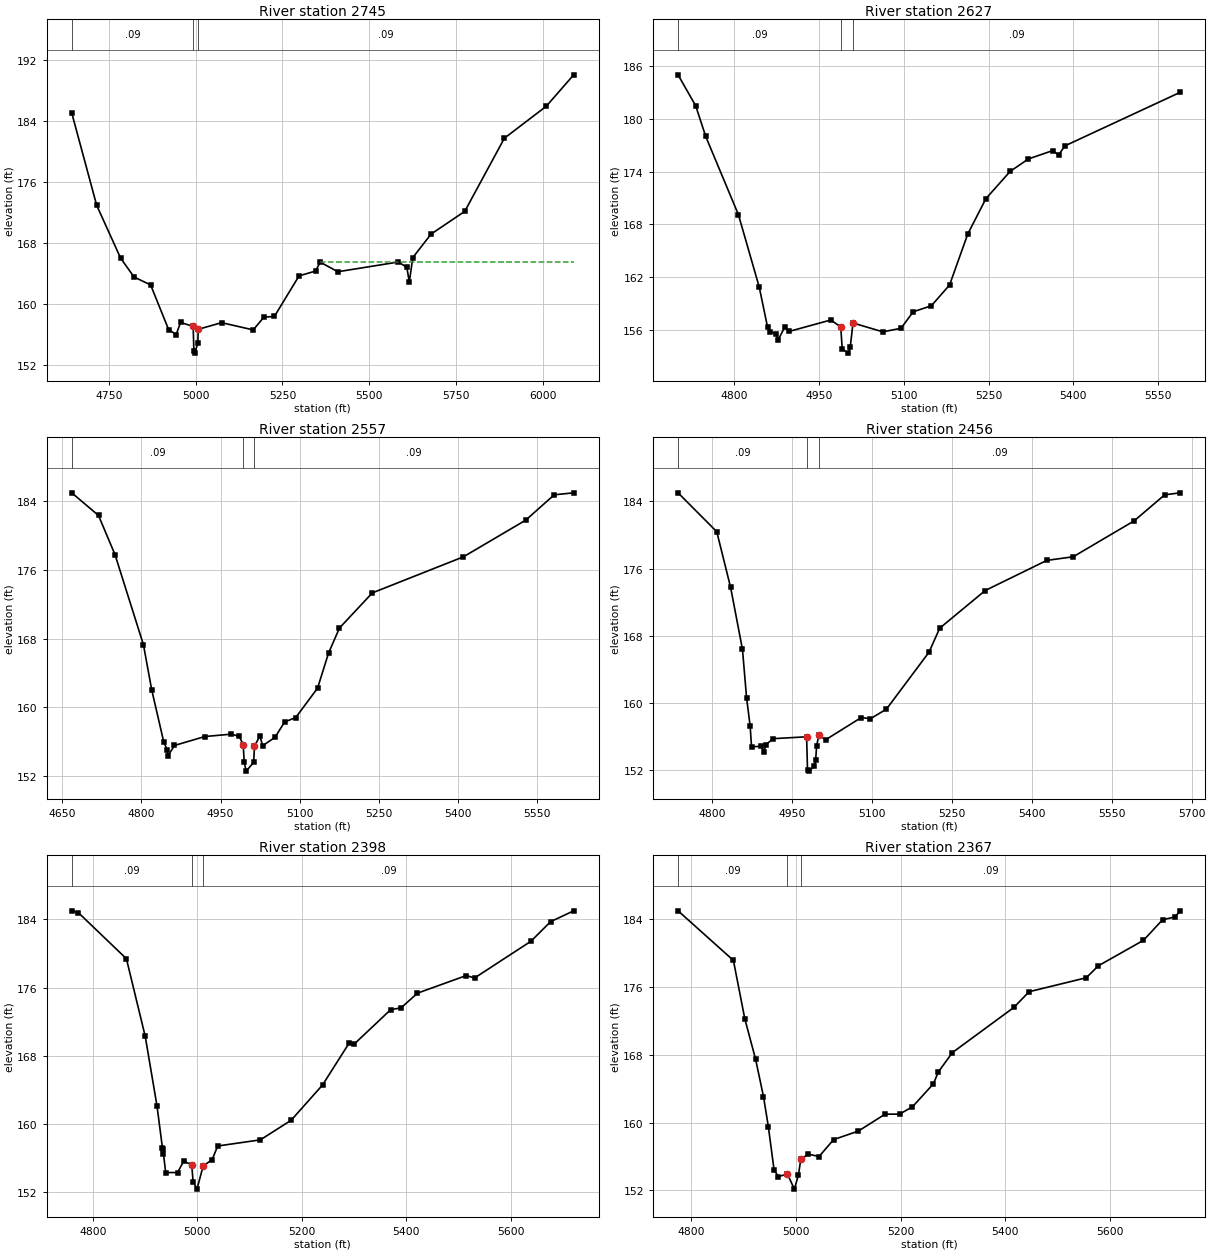
Type RM Length L Ch R = 1 ,2745    ,228.82,288.83,267.73
BEGIN DESCRIPTION:
Upstream NC 540
END DESCRIPTION:
XS GIS Cut Line= 5
    2146627.5999     721570.5221    2146471.2262     721809.0296
    2146414.6987     721840.0852    2146264.1795     722696.2867
    2146214.6696     722917.5896
#Sta/Elev= 30
 4643.01     185 4714.76  172.91 4783.74  165.99  4822.4  163.52 4870.23  162.48
 4921.95  156.64 4943.75  155.98 4956.38  157.57 4992.71  157.05 4994.71  153.89
  4997.1  153.55 5006.05  154.83 5007.37  156.67 5074.53  157.54  5165.8  156.59
 5196.27  158.26 5226.73  158.36 5297.82  163.67  5345.3   164.3 5358.74  165.46
 5409.51  164.21 5583.35  165.48 5608.14   164.8 5615.32  162.85 5625.28  166.06
 5677.95  169.14 5775.08  172.12 5889.21   181.7 6009.98  185.89 6088.81     190
#Mann= 3 ,0,0
 4643.01     .09       0 4992.71     .05       0 5007.37     .09       0
#XS Ineff= 2 , 0
                         5358.93          165.47
Permanent Ineff=
       F       F
Bank Sta=4992.71,5007.37
XS Rating Curve= 0 ,0
Exp/Cntr=0.3,0.1

Type RM Length L Ch R = 1 ,2627    ,33.02,69.68,54.06
XS GIS Cut Line= 4
    2146260.4035     721585.0244    2146283.2939      721739.144
    2146305.1418     721897.8888    2146100.9888     722430.6183
#Sta/Elev= 30
 4701.66     185 4732.91  181.46 4750.52  177.99 4808.33  169.08 4845.05  160.85
  4859.8  156.28 4864.74  155.77  4875.1  155.53 4878.54  154.86 4889.86  156.27
 4897.92  155.81 4971.51  157.11 4988.98  156.32 4991.66  153.79 5002.09  153.34
 5005.82  154.02 5010.62  156.77 5063.41  155.76 5095.54  156.17 5116.96  158.04
  5149.1  158.73 5181.23  161.09 5213.36  166.89 5245.49  170.92 5288.33  174.02
 5320.46  175.43  5363.3  176.38 5374.01  175.89 5384.72  176.91 5588.22     183
#Mann= 3 ,0,0
 4701.66     .09       0 4988.98     .05       0 5010.62     .09       0
#XS Ineff= 2 , 0
       0                  5227.9       0   163.5
Permanent Ineff=
       F       F
Bank Sta=4988.98,5010.62
XS Rating Curve= 0 ,0
Exp/Cntr=0.3,0.1

Type RM Length L Ch R = 1 ,2557    ,57.64,100.79,83.71
XS GIS Cut Line= 5
    2146240.4012     721570.1291    2146259.1841     721743.2648
    2146230.4001     721967.7213    2146167.8374     722193.0605
    2145983.7299     722450.6206
#Sta/Elev= 30
  4668.2     185 4718.89  182.36 4750.23  177.78 4804.02  167.29 4819.75  162.02
 4842.35     156 4848.94  155.06 4849.83  154.29 4862.75  155.56 4920.27   156.6
 4970.71  156.88 4985.64  156.61 4992.94  155.66 4994.93  153.62  4998.6  152.57
 5012.79  153.59 5014.37  155.47 5024.61  156.68 5029.82  155.53 5053.31  156.51
  5071.6  158.31 5092.36   158.8 5133.88  162.24 5154.64  166.32 5175.39  169.25
 5237.67  173.34 5410.12  177.54 5528.32  181.82 5582.22  184.77 5619.11     185
#Mann= 3 ,0,0
  4668.2     .09       0 4992.94     .05       0 5014.37     .09       0
#XS Ineff= 2 , 0
       0                  5172.5       0   163.5
Permanent Ineff=
       F       F
Bank Sta=4992.94,5014.37
XS Rating Curve= 0 ,0
Exp/Cntr=0.3,0.1

Type RM Length L Ch R = 1 ,2456    ,42.13,57.86,38.29
BEGIN DESCRIPTION:
Downstream NC 540
END DESCRIPTION:
XS GIS Cut Line= 5
    2146208.9537     721571.9662    2146197.2351      721802.771
    2146168.5301     721829.6033    2146164.1891     722191.5808
     2145983.788     722444.0353
#Sta/Elev= 30
 4735.44     185 4808.13  180.38 4834.13  173.76 4856.44  166.38 4864.18   160.6
  4870.9  157.24 4873.43  154.81 4891.24  154.87 4896.77   154.2 4900.22  155.06
 4914.25  155.78 4976.85     156  4978.6  152.02 4981.97  151.92 4991.67  152.57
 4993.83  153.21 4995.68   154.9 4999.79  156.21 5012.48  155.64 5079.54  158.29
  5096.8  158.15 5126.81  159.29 5206.82  166.06 5226.82  168.91 5312.38  173.39
 5428.08  176.97 5477.58   177.4  5592.1  181.67 5649.34  184.76 5678.13     185
#Mann= 3 ,0,0
 4735.44     .09       0 4976.85     .05       0 4999.79     .09       0
Bank Sta=4976.85,4999.79
XS Rating Curve= 0 ,0
Exp/Cntr=0.3,0.1

Type RM Length L Ch R = 1 ,2398    ,27.95,31.08,32.67
XS GIS Cut Line= 5
    2146183.2245     721537.6888    2146170.3402     721714.0857
    2146134.4481     721814.5992    2146157.3332     722184.8133
     2145984.022     722436.9696
#Sta/Elev= 30
 4759.93     185  4772.8  184.77 4864.51  179.38 4900.56  170.26 4923.02  162.12
 4933.52  157.16 4935.25  157.08 4935.45  156.48 4939.65   154.3 4962.31  154.29
 4973.94  155.61 4989.42  155.23 4992.19   153.2 4999.58  152.35 5011.27  155.05
 5028.61  155.82 5039.23  157.41 5120.81  158.13 5179.75  160.43 5239.87  164.57
 5290.67  169.48 5300.11  169.35 5370.14   173.4 5390.18  173.62 5421.46  175.34
 5514.99  177.41 5530.68  177.12 5638.58  181.43 5676.31  183.73 5720.42     185
#Mann= 3 ,0,0
 4759.93     .09       0 4989.42     .05       0 5011.27     .09       0
Bank Sta=4989.42,5011.27
XS Rating Curve= 0 ,0
Exp/Cntr=0.3,0.1

Type RM Length L Ch R = 1 ,2367    ,54.77,46.55,35.79
XS GIS Cut Line= 5
    2146183.1951     721536.4804    2146134.5129     721734.6518
    2146105.8556     721793.2239    2146150.3912     722184.8623
    2145982.9424     722428.0481
#Sta/Elev= 30
 4774.77     185 4880.47  179.15 4902.22  172.27 4922.85  167.48 4937.94  163.08
 4947.21  159.53 4958.14  154.42 4966.24  153.64  4983.8  153.92 4996.91  152.15
 5004.61  153.81 5009.24  155.67  5023.7  156.28 5044.04     156    5072     158
 5119.11     159 5170.19     161 5197.86     161 5222.53  161.87 5262.62  164.59
 5271.66  165.96 5298.78  168.27 5416.27   173.6 5445.16  175.45 5554.44   177.1
 5577.51  178.51 5663.73  181.52 5700.16  183.94 5724.44  184.29 5733.46     185
#Mann= 3 ,0,0
 4774.77     .09       0  4983.8     .05       0 5009.24     .09       0
Bank Sta=4983.8,5009.24
XS Rating Curve= 0 ,0
Exp/Cntr=0.3,0.1

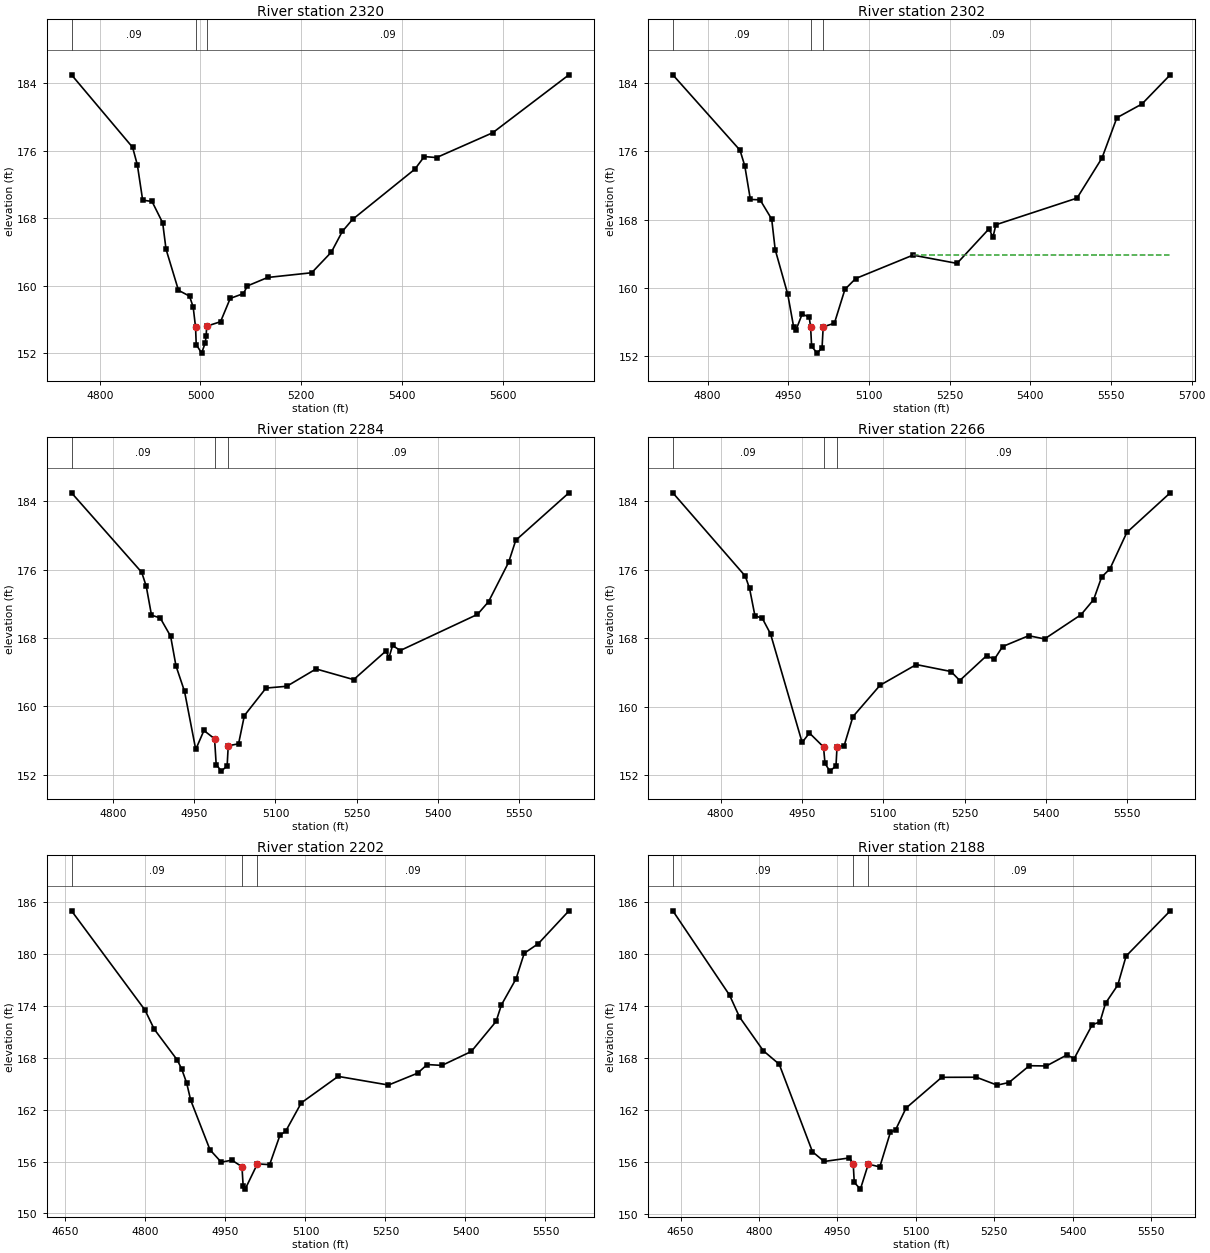
Type RM Length L Ch R = 1 ,2320    ,20.15,18.14,17.99
BEGIN DESCRIPTION:
Upstream Y29RPA
END DESCRIPTION:
XS GIS Cut Line= 5
    2146183.1592     721535.0024    2146077.9739     721655.3242
    2146083.7517     721832.7586    2146140.2657     722186.8835
    2145974.2538     722426.7355
#Sta/Elev= 30
 4743.94     185 4865.25  176.41  4874.7  174.31 4885.18  170.16 4903.76     170
 4924.94  167.47 4931.56  164.35 4956.28  159.48 4978.25  158.79 4985.51  157.49
 4990.22   155.1 4991.53  153.06 5002.25  152.04 5009.31  153.24 5011.28  154.07
 5012.25  155.23 5039.82  155.76 5059.06  158.52 5085.15  159.09  5093.2     160
 5133.37     161 5220.84  161.56 5259.83     164  5281.6  166.45 5301.86  167.87
 5425.77  173.83  5444.4  175.32 5468.73   175.2 5580.26  178.14 5731.59     185
#Mann= 3 ,0,0
 4743.94     .09       0 4990.22     .05       0 5012.25     .09       0
Bank Sta=4990.22,5012.25
XS Rating Curve= 0 ,0
Exp/Cntr=0.3,0.1

Type RM Length L Ch R = 1 ,2302    ,18.12,18.15,20.25
XS GIS Cut Line= 5
    2146183.1045     721532.7498      2146076.06     721654.2456
     2146061.911     721711.3429    2146066.2089     721840.9524
    2145672.5249     722259.2793
#Sta/Elev= 30
 4735.25     185  4860.2  176.14 4869.08  174.29 4879.42  170.36 4897.43  170.32
 4919.08  168.05 4925.57  164.47 4948.88  159.24 4959.91  155.38 4964.37  155.05
 4975.73   156.9 4988.79  156.54 4991.43  155.39 4993.32  153.11 5003.59  152.31
 5012.72  152.94 5014.84   155.4 5035.66  155.82 5055.26   159.8 5075.27  161.07
 5181.74  163.82 5263.67  162.85 5323.16  166.91  5330.5  165.92 5335.94  167.39
 5486.84  170.52 5533.29  175.23 5560.92  179.96 5607.49  181.57 5660.12     185
#Mann= 3 ,0,0
 4735.25     .09       0 4991.43     .05       0 5014.84     .09       0
#XS Ineff= 2 , 0
                         5181.62          163.84
Permanent Ineff=
       F       F
Bank Sta=4991.43,5014.84
XS Rating Curve= 0 ,0
Exp/Cntr=0.3,0.1

Type RM Length L Ch R = 1 ,2284    ,19.7,18.14,18.29
XS GIS Cut Line= 5
    2146183.0225     721530.4369    2146071.8015     721653.8001
    2146045.6589     721700.8599     2146045.363     721846.6753
    2145672.3905     722256.2593
#Sta/Elev= 30
 4722.94     185 4852.69  175.69 4861.09  174.05  4870.8  170.67 4886.92  170.34
 4906.16   168.2 4916.11  164.72 4931.89  161.74 4952.58  154.94 4967.78  157.16
  4987.4  156.19 4990.42  153.17 5000.09   152.4 5010.69  153.03  5012.7  155.37
 5031.78   155.6 5042.56  158.91 5082.56  162.13 5120.99  162.34 5175.09  164.37
 5244.63  163.12 5304.26  166.47 5310.01   165.7 5316.54  167.12 5330.86  166.53
 5473.53  170.76 5494.05  172.25 5531.21  176.87 5544.34  179.44 5642.64     185
#Mann= 3 ,0,0
 4722.94     .09       0  4987.4     .05       0  5012.7     .09       0
Bank Sta=4987.4,5012.7
XS Rating Curve= 0 ,0
Exp/Cntr=0.3,0.1

Type RM Length L Ch R = 1 ,2266    ,61.93,64.27,65.62
XS GIS Cut Line= 4
    2146182.3702     721528.5419    2146027.6835     721697.6024
    2146027.1045     721850.5235    2145672.1564     722250.9953
#Sta/Elev= 30
 4711.91     185 4845.47  175.28  4853.4  173.84 4863.26  170.66    4877  170.34
 4892.09  168.53 4950.35  155.86  4963.8  156.96 4989.81  155.33 4992.49  153.41
 5001.47  152.51 5012.78  153.12 5014.68  155.33 5027.79  155.48 5044.01  158.87
 5093.98  162.53 5160.84  164.95 5224.75  164.14 5241.03  163.09 5290.55  165.99
 5304.75  165.56    5320  167.05 5368.17  168.32 5397.36  167.94  5464.6  170.77
 5487.87  172.53 5502.66  175.17 5517.93  176.12 5549.17  180.38 5629.11     185
#Mann= 3 ,0,0
 4711.91     .09       0 4989.81     .05       0 5014.68     .09       0
Bank Sta=4989.81,5014.68
XS Rating Curve= 0 ,0
Exp/Cntr=0.3,0.1

Type RM Length L Ch R = 1 ,2202    ,28.58,13.98,9.63
XS GIS Cut Line= 4
    2146181.0231     721519.8878    2145965.9104     721674.9938
    2145960.3699     721865.7692     2145670.305     722243.9266
#Sta/Elev= 30
 4661.36     185 4799.23  173.51 4816.33  171.32 4859.41  167.76 4867.64  166.75
 4877.19   165.1 4884.73  163.11 4921.06  157.35 4942.11  155.93 4962.12  156.16
 4980.93   155.4 4983.22  153.12 4986.96  152.81 5009.83  155.73 5032.81  155.64
 5052.17  159.04 5063.03  159.52 5092.19  162.79 5161.26  165.85 5255.66  164.85
 5310.18  166.22 5328.29  167.22 5355.91  167.12 5410.94  168.73 5457.48  172.21
 5467.36  174.11 5494.91  177.14 5510.22  180.09 5536.76  181.21 5594.01     185
#Mann= 3 ,0,0
 4661.36     .09       0 4980.93     .05       0 5009.83     .09       0
Bank Sta=4980.93,5009.83
XS Rating Curve= 0 ,0
Exp/Cntr=0.3,0.1

Type RM Length L Ch R = 1 ,2188    ,25.1,14,9.52
XS GIS Cut Line= 4
    2146177.5037     721513.4062    2145946.2389     721656.5621
     2145954.374     721856.8536    2145669.5678     722242.0678
#Sta/Elev= 30
 4635.31     185 4743.83  175.27 4762.83  172.75 4808.34  168.86 4838.83   167.3
 4902.44   157.2 4924.71  156.08 4973.06  156.49  4980.4  155.82 4982.36  153.67
 4994.15  152.89 5009.25  155.78 5031.21  155.45  5051.4  159.43 5061.66  159.76
 5081.43  162.24 5149.67  165.79    5216   165.8 5255.57  164.89  5278.4  165.19
 5317.28  167.13 5349.91   167.1 5389.16  168.37 5403.16  167.96 5437.59  171.85
 5452.51  172.19 5463.08  174.34 5486.45  176.43 5502.42  179.78 5586.82     185
#Mann= 3 ,0,0
 4635.31     .09       0  4980.4     .05       0 5009.25     .09       0
Bank Sta=4980.4,5009.25
XS Rating Curve= 0 ,0
Exp/Cntr=0.3,0.1

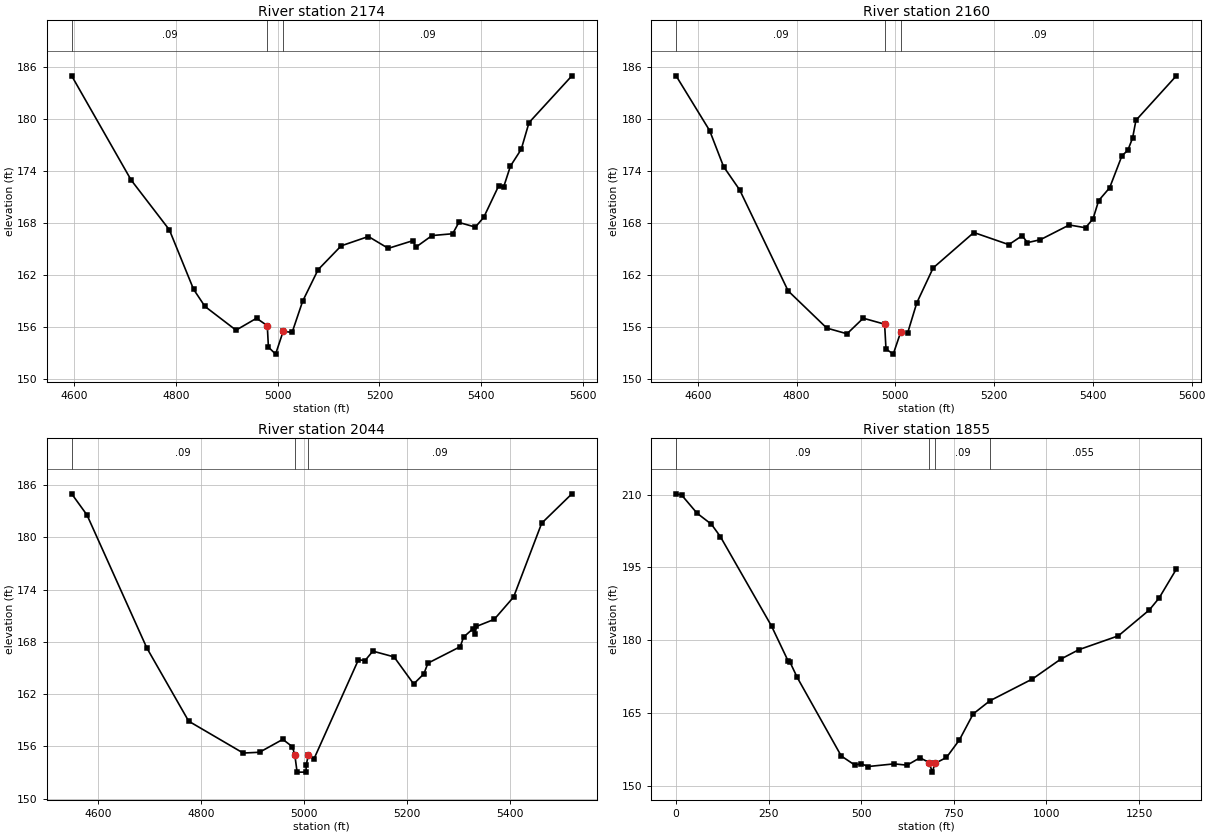
Type RM Length L Ch R = 1 ,2174    ,32.06,14,8.31
XS GIS Cut Line= 4
    2146175.1341     721505.7747    2145921.6675      721630.562
    2145947.7235     721847.4336    2145669.1719     722240.1963
#Sta/Elev= 30
 4595.58     185 4712.34  172.95 4787.45  167.19 4834.96  160.32 4857.26  158.34
 4918.36  155.59 4958.65  156.97 4979.78  156.11 4982.01  153.63  4996.1  152.82
 5010.98  155.46 5028.54  155.33 5049.31  158.95 5079.53  162.58 5124.88  165.34
  5178.4  166.42 5217.39  165.05  5265.8  165.94 5271.64  165.19 5303.31  166.53
 5343.87  166.74 5356.04  168.05 5388.43  167.51 5404.92  168.64 5434.09  172.26
 5443.95  172.14 5457.34  174.56 5478.58  176.51 5493.83  179.59 5578.04     185
#Mann= 3 ,0,0
 4595.58     .09       0 4979.78     .05       0 5010.98     .09       0
Bank Sta=4979.78,5010.98
XS Rating Curve= 0 ,0
Exp/Cntr=0.3,0.1

Type RM Length L Ch R = 1 ,2160    ,37.12,115.18,131.66
BEGIN DESCRIPTION:
Downstream Y29RPA
END DESCRIPTION:
XS GIS Cut Line= 4
     2146168.594     721497.7175    2145891.1636     721617.7107
    2145942.0606     721838.8593    2145668.7487     722238.1953
#Sta/Elev= 30
 4555.87     185 4623.85  178.67 4651.98  174.52 4684.67  171.82 4782.74  160.16
 4861.03  155.86 4902.08   155.2  4934.9     157 4978.21  156.31 4980.97  153.45
 4995.67  152.85 5011.08  155.44 5024.66  155.26 5043.36  158.77 5076.54  162.81
  5158.9   166.9  5229.8   165.5 5256.78  166.53 5267.59  165.73  5293.7  166.07
 5352.13  167.77 5385.09  167.45 5400.34  168.48 5411.74  170.59 5433.89  172.06
 5458.91  175.77 5470.69  176.39 5480.45  177.81 5487.21  179.86 5568.98     185
#Mann= 3 ,0,0
 4555.87     .09       0 4978.21     .05       0 5011.08     .09       0
Bank Sta=4978.21,5011.08
XS Rating Curve= 0 ,0
Exp/Cntr=0.3,0.1

Type RM Length L Ch R = 1 ,2044    ,129.53,189.35,207.74
XS GIS Cut Line= 3
     2146157.513     721460.4359    2145875.9067      721587.631
     2145661.187     722214.6296
#Sta/Elev= 30
 4548.37     185 4578.13  182.57 4694.33  167.31 4775.66   158.9 4881.57  155.24
 4913.28  155.33 4958.51  156.81 4977.03  155.97 4981.81  155.04  4986.3  153.05
 5003.62  153.05 5003.95  153.86 5008.26  155.03 5018.78  154.53 5105.43  165.95
 5118.27  165.86 5133.48  166.94 5174.61  166.28 5212.76  163.17 5232.51  164.33
 5240.46  165.56 5303.14  167.45  5309.8  168.56 5328.22  169.52 5332.33  168.96
 5334.78  169.78 5369.27  170.59 5406.87  173.15 5461.48  181.63 5520.12     185
#Mann= 3 ,0,0
 4548.37     .09       0 4981.81     .05       0 5008.26     .09       0
Bank Sta=4981.81,5008.26
XS Rating Curve= 0 ,0
Exp/Cntr=0.3,0.1

Type RM Length L Ch R = 1 ,1855    ,359.89,398.72,297.29
XS GIS Cut Line= 2
2146192.77551657721126.7807490832145206.96859962722050.073351085
#Sta/Elev= 30
       0  210.14   14.73  209.91   56.63  206.15    95.4  203.88  119.43  201.35
  257.64  182.94  302.79   175.7  307.46  175.53  327.13  172.35  445.98   156.2
  482.45  154.34  500.22   154.6   518.3  154.03   588.7  154.58  623.69  154.31
  658.51  155.83   683.3  154.86  691.69  152.88  699.29  154.69     730  155.89
  764.95   159.5  802.13  164.85  847.13  167.55   962.3  172.05 1038.87  176.14
 1087.45  178.07 1194.38  180.93 1277.97  186.26 1304.05  188.68 1350.66  194.63
#Mann= 4 ,-1,0
       0     .09       0   683.3     .05       0  699.29     .09       0
  847.13    .055       0
Bank Sta=683.3,699.29
XS Rating Curve= 0 ,0
Exp/Cntr=0.3,0.1